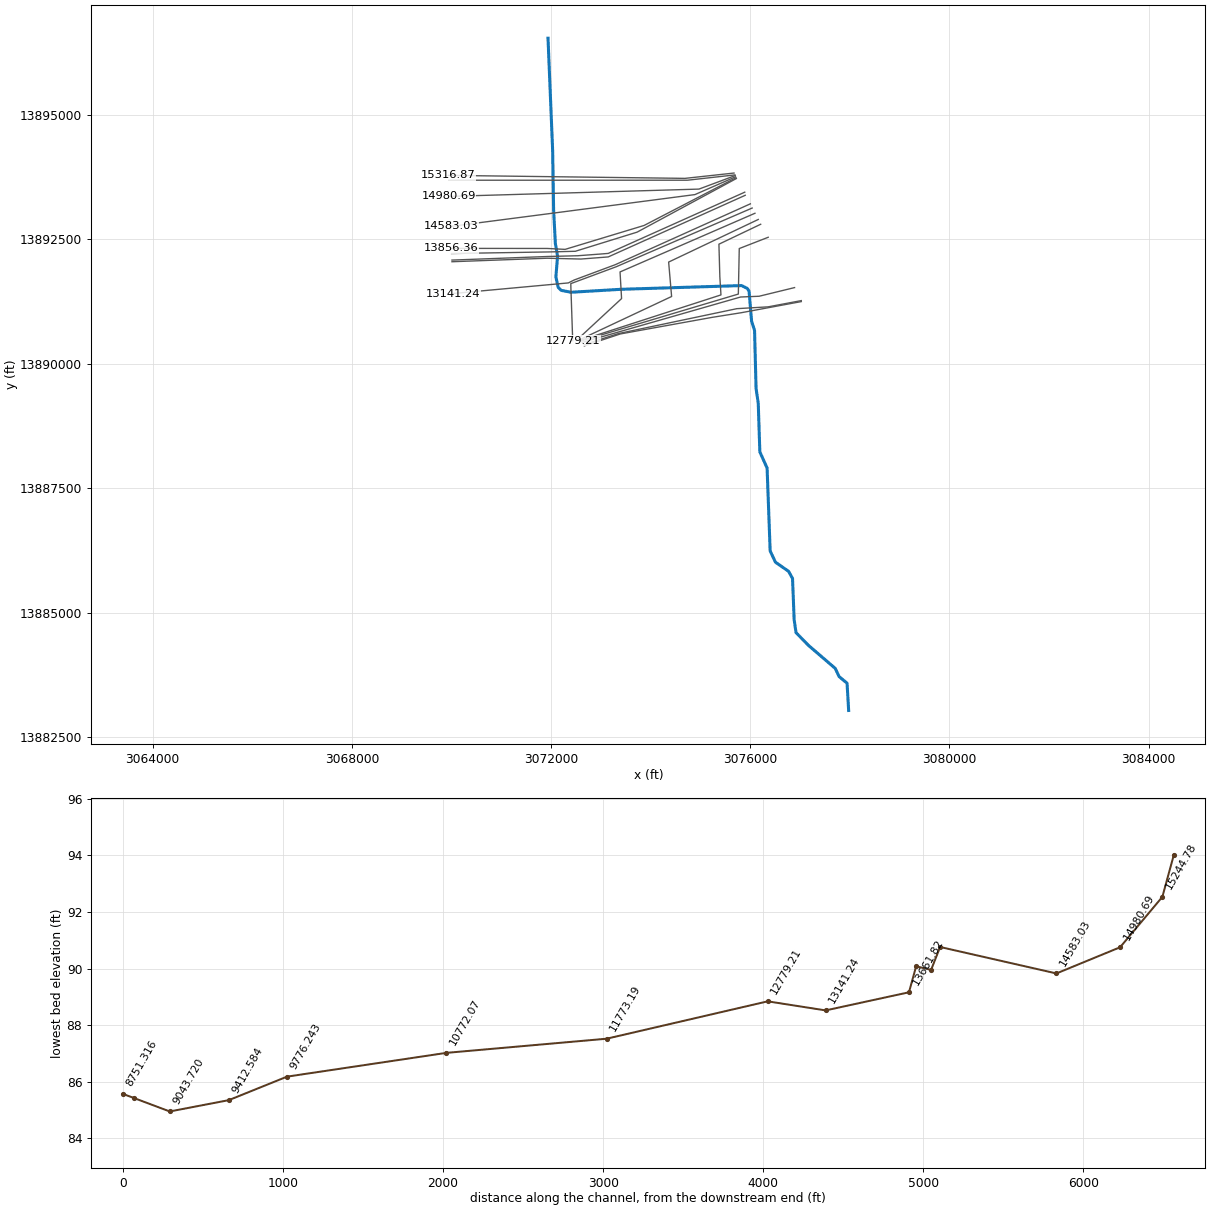
--- E122-00-00.prj (project) ---

Proj Title=E122-00-00
Current Plan=p06
Default Exp/Contr=.3,.1
English Units
Geom File=g08
Flow File=f04
Flow File=f05
Plan File=p06
Plan File=p02
Y Axis Title=Elevation
X Axis Title(PF)=Main Channel Distance
X Axis Title(XS)=Station
BEGIN DESCRIPTION:
Watershed: White Oak Bayou
Stream Name: unnamed tributary to White Oak Bayou
HCFCD Unit E122-00-00
(Flood Hazard, Floodway) Model
10, 2, 1, .02% Event
File Name: E122-00-00.prj
Prepared by:  Ty Turner, Sean Sutton (TCB revisions) 6/10/03
Reviewed by: Joe Barrow
Status: Final RAS
END DESCRIPTION:
DSS Export Rating Curves= 0
DSS Export Rating Curve Sorted= 0
DSS Export Volume Flow Curves= 0
DXF OffsetX= 0
DXF OffsetY= 0
DXF ScaleX= 1
DXF ScaleY= 10

--- E122-00-00.p06 (plan) ---

Plan Title=FEMA Effective June 2007
Version=Version 3.0.1  Mar 2001
Short Identifier=FEMAeff0607
Geom File=g08
Flow File=f04
Subcritical Flow
K Sum by GR= 0
Std Step Tol= 0.01
Critical Tol= 0.01
Num of Std Step Trials= 20
Max Error Tol= 0.3
Flow Tol Ratio= 0.001
Split Flow NTrial= 30
Split Flow Tol= 0.02
Split Flow Ratio= 0.02
Log Output Level= 0
Friction Slope Method= 0
Unsteady Friction Slope Method= 2
Secant Critical Depth
Global Vel Dist= 0 , 0 , 0
Global Log Level= 0
CheckData=True
Encroach Param=-1 ,0,0, 2
Computation Interval=1HOUR
Output Interval=1HOUR
Run HTab= 0
Run UNet= 0
Run PostProcess= 0
UNET Theta= 1
UNET ZTol= 0.02
UNET ZSATol= 0.1
UNET MxIter= 20
UNET MaxInSteps= 20
UNET DtIC= 0
UNET DtMin= 0
UNET MaxCRTS= 20
UNET WFStab= 2
UNET SFStab= 1
UNET WFX= 1
UNET SFX= 1
UNET Convert EG Bridges=-1
UNET Use Existing IB Tables=-1
Instantaneous Interval=1HOUR
DSS File=dss
Write IC File= 0
IC Time=0
Write Velocity= 0
Write Detailed= 0

--- E122-00-00.p02 (plan) ---

Plan Title=Floodway
Version=Version 3.0.1  Mar 2001
Short Identifier=Floodway0607
Geom File=g08
Flow File=f05
Subcritical Flow
K Sum by GR= 0
Std Step Tol= 0.01
Critical Tol= 0.01
Num of Std Step Trials= 20
Max Error Tol= 0.3
Flow Tol Ratio= 0.001
Split Flow NTrial= 30
Split Flow Tol= 0.02
Split Flow Ratio= 0.02
Log Output Level= 0
Friction Slope Method= 0
Unsteady Friction Slope Method= 2
Secant Critical Depth
Global Vel Dist= 0 , 0 , 0
Global Log Level= 0
CheckData=True
Encroach Param=-1 ,0,0, 2
Encroach River=E122-00-00
Encroach Reach=E122-00-00_0000
Encroach Node=15316.87
       1 3611.96 3635.93
Encroach Node=15244.78
       1 3597.09 3679.09
Encroach Node=14980.69
       1 3624.54 3709.56
Encroach Node=14583.03
       1 3675.09 3756.53
Encroach Node=13856.36
       1 3821.34 3944.64
Encroach Node=13799.94
       1 3852.72 4002.43
Encroach Node=13754.94
       1 3923.52 4080.97
Encroach Node=13706.71
       1 3923.52 4080.97
Encroach Node=13661.82
       1 3965.62 4095.77
Encroach Node=13141.24
       1 4127.37 4229.76
Encroach Node=12779.21
       1 4045.27 4148.38
Encroach Node=11773.19
       1 3255.75 3356.98
Encroach Node=10772.07
       1 2443.73  2548.2
Encroach Node=9776.243
       1 1688.05 1792.28
Encroach Node=9412.584
       1 1291.29 1402.31
Encroach Node=9043.720
       1  821.61  930.76
Encroach Node=8817.703
       1  936.32 1055.41
Encroach Node=8751.316
       1  954.58 1068.79
Encroach Node=8747.55
       1  989.33 1120.14
Encroach Node=8706.955
       1  989.33 1120.14
Encroach Node=8630.772
       1 1036.09 1145.34
Encroach Node=8090.234
       1  1240.4 1354.92
Encroach Node=7366.673
       1 1652.34 1741.61
Encroach Node=7323.165
       1 1695.64 1780.64
Encroach Node=7296.664
       1 1107.64 2233.64
Encroach Node=7268.812
       1 1715.38 1809.38
Encroach Node=7249.799
       1 1728.43 1848.44
Encroach Node=6898.815
       1 1865.74 1949.85
Encroach Node=5983.005
       1 2265.55 2347.31
Encroach Node=5431.968
       1 2267.87 2341.36
Encroach Node=5380
       4       1
Encroach Node=5348.006
       1 2403.54 2499.54
Encroach Node=5267.653
       1 2397.92 2492.92
Encroach Node=4762.511
       1 2362.61 2470.62
Encroach Node=4689.561
       1  2359.4 2465.53
Encroach Node=4668.847
       1 2326.63 2467.86
Encroach Node=4648.134
       1 2326.63 2467.86
Encroach Node=4575.253
       1 2326.56 2483.56
Encroach Node=4230.466
       1 2329.89 2435.96
Encroach Node=3860.318
       1 2314.37 2423.06
Encroach Node=3809.425
       1 2299.79 2406.11
Encroach Node=3766.214
       1 2259.38 2409.28
Encroach Node=3049.070
       1  1626.4 1723.47
Encroach Node=2998.224
       1 1609.95 1710.26
Encroach Node=2111.142
       1 1391.51 1504.87
Encroach Node=2063.198
       1 1383.51 1498.45
Encroach Node=1748.955
       1 1286.99  1395.2
Encroach Node=1040.148
       1  883.52  987.78
Encroach Node=645.763
       1  520.08  616.15
Encroach Node=514.233
       1  257.29  335.35
Encroach Node=471.314
       1  212.29  327.92
Encroach Node=423.395
       1  212.29  327.92
Encroach Node=279.778
       1  163.39  268.64
Encroach Node=3.533
       1   89.99  192.71
Computation Interval=1HOUR
Output Interval=1HOUR
Run HTab= 0
Run UNet= 0
Run PostProcess= 0
UNET Theta= 1
UNET ZTol= 0.02
UNET ZSATol= 0.1
UNET MxIter= 20
UNET MaxInSteps= 20
UNET DtIC= 0
UNET DtMin= 0
UNET MaxCRTS= 20
UNET WFStab= 2
UNET SFStab= 1
UNET WFX= 1
UNET SFX= 1
UNET Convert EG Bridges=-1
UNET Use Existing IB Tables=-1
Instantaneous Interval=1HOUR
DSS File=dss
Write IC File= 0
IC Time=0
Write Velocity= 0
Write Detailed= 0

--- E122-00-00.f04 (steady flow) ---

Flow Title=FEMA Effective June 2007
Program Version=3.13
Number of Profiles= 4
Profile Names=10PCT_10yr,2PCT_50yr,1PCT_100yr,0.2PCT_500yr
River Rch & RM=E122-00-00,E122-00-00_0000            ,15316.87
    1212    1783    2072    2893
River Rch & RM=E122-00-00,E122-00-00_0000            ,14583.03
    1284    1890    2198    3072
River Rch & RM=E122-00-00,E122-00-00_0000            ,13799.94
    1355    1997    2323    3251
River Rch & RM=E122-00-00,E122-00-00_0000            ,12779.21
    1422    2099    2443    3423
River Rch & RM=E122-00-00,E122-00-00_0000            ,10772.07
    1496    2210    2573    3610
River Rch & RM=E122-00-00,E122-00-00_0000            ,8751.316
    1569    2322    2704    3798
River Rch & RM=E122-00-00,E122-00-00_0000            ,7366.673
    1653    2449    2853    4015
River Rch & RM=E122-00-00,E122-00-00_0000            ,5983.005
    1744    2588    3017    4252
River Rch & RM=E122-00-00,E122-00-00_0000            ,4689.561
    1830    2719    3172    4477
River Rch & RM=E122-00-00,E122-00-00_0000            ,3049.070
    1926    2868    3347    4733
River Rch & RM=E122-00-00,E122-00-00_0000            ,1040.148
    2023    3018    3525    4993
Boundary for River Rch & Prof#=E122-00-00,E122-00-00_0000            , 1
Up Type= 0
Dn Type= 3
Dn Slope=0.0012
DSS Import GetInterval= 0
DSS Import GetPeak= 0
DSS Import FillOption= 0
DSS File=V:\TSARP\4-EngCal\HydrologicModels\Klotz\E100_100_02\E100_100_02.dss

--- E122-00-00.f05 (steady flow) ---

Flow Title=Floodway
Program Version=3.13
Number of Profiles= 2
Profile Names=1PCT_100yr,1PCTFloodway_100yrFW
River Rch & RM=E122-00-00,E122-00-00_0000            ,15316.87
    2072    2072
River Rch & RM=E122-00-00,E122-00-00_0000            ,14583.03
    2198    2198
River Rch & RM=E122-00-00,E122-00-00_0000            ,13799.94
    2323    2323
River Rch & RM=E122-00-00,E122-00-00_0000            ,12779.21
    2443    2443
River Rch & RM=E122-00-00,E122-00-00_0000            ,10772.07
    2573    2573
River Rch & RM=E122-00-00,E122-00-00_0000            ,8751.316
    2704    2704
River Rch & RM=E122-00-00,E122-00-00_0000            ,7366.673
    2853    2853
River Rch & RM=E122-00-00,E122-00-00_0000            ,5983.005
    3017    3017
River Rch & RM=E122-00-00,E122-00-00_0000            ,4689.561
    3172    3172
River Rch & RM=E122-00-00,E122-00-00_0000            ,3049.070
    3347    3347
River Rch & RM=E122-00-00,E122-00-00_0000            ,1040.148
    3525    3525
Boundary for River Rch & Prof#=E122-00-00,E122-00-00_0000            , 1
Up Type= 0
Dn Type= 3
Dn Slope=0.0012
DSS Import GetInterval= 0
DSS Import GetPeak= 0
DSS Import FillOption= 0
DSS File=V:\TSARP\4-EngCal\HydrologicModels\Klotz\E100_100_02\E100_100_02.dss

--- E122-00-00.g08 (geometry) ---

Geom Title=E122-00-00 June 2007
Program Version=3.13

River Reach=E122-00-00      ,E122-00-00_0000
Reach XY= 30
     3071939.998    13896538.211     3072033.296    13894278.999
      3072052.64    13893084.268     3072087.297    13892418.796
     3072131.974    13892160.224     3072098.043    13891745.265
     3072145.865    13891531.949     3072204.164    13891474.993
     3072403.134    13891437.132     3073405.859    13891496.449
     3075827.853    13891571.174     3075940.153    13891514.218
     3075976.959    13891462.097     3076028.004    13890856.269
     3076087.647    13890668.475     3076117.737    13889507.595
     3076161.783    13889207.721     3076193.768    13888231.459
     3076339.382    13887908.261     3076400.853    13886243.048
     3076507.831    13886016.087     3076770.581    13885833.936
     3076850.105    13885691.546     3076882.612    13884863.804
     3076920.575    13884601.968     3077174.109    13884343.409
      3077707.13    13883884.806     3077786.923    13883718.774
     3077945.432    13883586.862     3077976.925    13883039.714

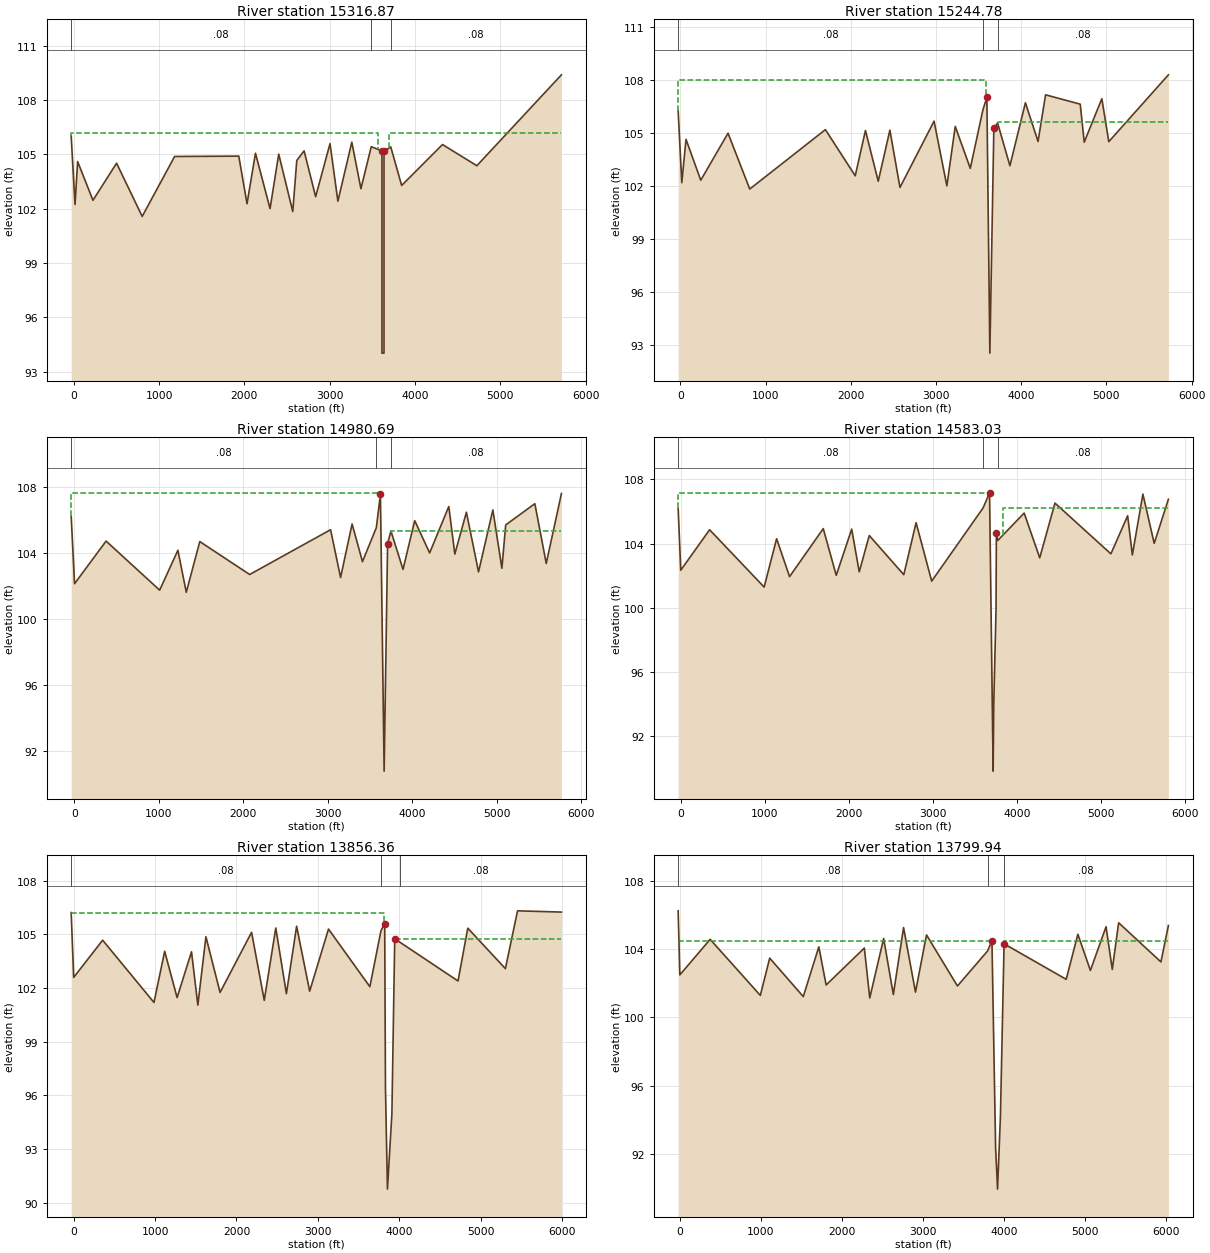
Type RM Length L Ch R = 1 ,15316.87,72.49,72.06,71.11
BEGIN DESCRIPTION:
E122-00-S5 (Survey 3611.96 to 3635.93) XS 2
Data inserted from bridge survey
Point deleted 149.94
END DESCRIPTION:
XS GIS Cut Line= 6
 3075675.648655713893830.6680771     3074690.159    13893723.694
     3072181.863    13893755.295     3072081.871    13893756.568
        3071891.       13893759.      3069935.56     13893783.91
#Sta/Elev= 30
  -30.71  106.01   14.74  102.23   44.92   104.6  224.53  102.46  501.37  104.51
  801.59  101.57 1181.86  104.88  1933.8   104.9 2030.35  102.27  2129.5  105.06
 2300.37     102 2401.97  105.01 2566.48  101.84 2613.59  104.66 2699.26  105.19
 2834.67  102.66 3003.11  105.59 3095.43  102.41 3258.63  105.67 3365.45   103.1
 3486.49  105.42 3611.96  105.19 3611.97   94.02 3635.87   94.02 3635.93  105.16
 3715.11  105.41 3842.72  103.28 4321.51  105.54  4724.2  104.37 5715.55  109.39
#Mann= 3 ,-1 , 0
  -30.71     .08       0 3486.49     .04       0 3715.11     .08       0
#XS Ineff= 2 , 0
         3559.96  106.19 3692.64          106.19
Permanent Ineff=
       F       F
Bank Sta=3611.96,3635.93
Exp/Cntr=0.5,0.3

Type RM Length L Ch R = 1 ,15244.78,262.96,264.1,265.65
BEGIN DESCRIPTION:
E122-00-SV5 (Survey 3585.09 to 3707.09) XS 1
END DESCRIPTION:
XS GIS Cut Line= 5
  3075692.20615813893793.1128294     3075667.331    13893790.333
     3074741.802    13893686.904     3072211.971    13893686.528
     3069945.965    13893686.528
#Sta/Elev= 30
  -25.03  106.25   17.79  102.17   67.28  104.62  240.34  102.31  560.23  104.97
  814.99  101.81 1702.64  105.17 2052.63  102.56 2172.63  105.12 2322.63  102.25
 2459.31  105.14 2577.63   101.9 2977.67  105.65 3127.71  101.99 3226.25  105.35
 3402.63  102.98 3550.82  106.29 3597.09  106.99 3632.09   92.53 3679.09  105.24
 3722.63  105.55 3867.63  103.13 4049.36  106.69 4197.63   104.5 4285.89  107.14
 4692.63  106.61 4739.36  104.46  4946.1  106.92 5027.84  104.49 5727.13  108.27
#Mann= 3 ,-1 , 0
  -25.03     .08       0 3550.82     .04       0 3722.63     .08       0
#XS Ineff= 2 , 0
         3584.74     108 3726.19          105.59
Permanent Ineff=
       F       F
Bank Sta=3597.09,3679.09
Exp/Cntr=0.3,0.1

Type RM Length L Ch R = 1 ,14980.69,390.82,397.66,403.94
BEGIN DESCRIPTION:
E122-00-V6 (Survey 3558.51 to 3709.56)
END DESCRIPTION:
XS GIS Cut Line= 6
 3075699.013712913893779.8662546     3074971.134    13893508.359
     3072261.131    13893428.957     3071982.309    13893420.836
     3071882.351    13893417.925     3069945.831    13893361.521
#Sta/Elev= 30
   -36.7  106.23    3.47  102.13  376.54  104.72 1010.95  101.74 1226.77  104.16
 1326.09  101.61 1486.05  104.69 2076.41  102.69 3034.44  105.41 3152.88  102.51
 3289.29  105.76 3411.98  103.47 3575.92  105.53 3624.54  107.56 3668.55   90.75
 3709.56  104.56 3748.95  105.33 3892.19     103 4030.46  105.96 4207.32     104
 4434.14  106.82 4505.33  103.93 4642.51  106.47 4786.24  102.85  4955.8  106.61
 5062.68  103.07  5107.7   105.7 5452.85  106.99 5587.91  103.36 5767.62  107.61
#Mann= 3 ,-1 , 0
   -36.7     .08       0 3575.92     .04       0 3748.95     .08       0
#XS Ineff= 2 , 0
          3614.7  107.65 3744.02          105.33
Permanent Ineff=
       F       F
Bank Sta=3624.54,3709.56
Exp/Cntr=0.3,0.1

Type RM Length L Ch R = 1 ,14583.03,732.35,726.67,717.31
BEGIN DESCRIPTION:
E122-00-SV6 (Survey 3663.06 to 3764.59) Pipeline location
END DESCRIPTION:
XS GIS Cut Line= 6
  3075705.477327 13893754.858261     3074889.887    13893397.909
     3072220.401    13893048.774     3072121.233    13893035.902
     3071901.664      13893007.4     3069986.569    13892758.806
#Sta/Elev= 30
  -31.13  106.19       0  102.34   343.3  104.86   992.3  101.29 1140.75   104.3
 1295.04  101.94 1695.98  104.93 1850.74  102.02 2034.44   104.9 2124.26  102.24
 2243.73   104.5 2654.57  102.06 2800.84   105.3 2986.67  101.66 3598.45  106.22
 3675.09  107.15 3717.97 89.8253 3724.95 93.9222 3752.37 99.9283 3756.53  104.63
 3772.56  104.19 4087.29   105.9 4272.31  103.11 4453.82  106.52 5119.35  103.36
 5318.82  105.73 5374.94  103.29 5500.48  107.08 5634.92  104.01 5803.94  106.76
#Mann= 3 ,-1 , 0
  -31.13     .08       0 3598.45     .04       0 3772.56     .08       0
#XS Ineff= 2 , 0
         3674.54  107.16 3831.99          106.19
Permanent Ineff=
       F       F
Bank Sta=3675.09,3756.53
Exp/Cntr=0.3,0.1

Type RM Length L Ch R = 1 ,13856.36,52.79,56.42,60.96
BEGIN DESCRIPTION:
E122-00-SV7 (Survey 3814.35 to 3944.64) XS 4
END DESCRIPTION:
XS GIS Cut Line= 6
 3075713.734643213893735.0764969        3073869.    13892778.117
     3072283.034    13892297.882     3072027.459    13892311.183
     3071927.594     13892316.38      3069994.81    13892318.044
#Sta/Elev= 30
  -31.01  106.21       0  102.59  355.74  104.67  986.39  101.19  1117.8  104.05
 1270.47  101.46 1447.61  104.02 1525.41  101.04 1624.69  104.86 1798.61  101.75
 2185.79  105.11 2341.38  101.31 2483.18  105.35 2613.62  101.68 2739.02  105.45
 2899.47  101.82 3130.87  105.29 3639.02  102.07 3775.56   105.2 3821.34   105.6
 3830.77   96.42 3855.07   90.76 3909.79   94.98 3944.64  104.75 4010.24  104.55
  4722.3  102.39  4842.3  105.34 5304.44  103.08 5453.85  106.31 5992.95  106.24
#Mann= 3 ,-1 , 0
  -31.01     .08       0 3775.56     .04       0 4010.24     .08       0
#XS Ineff= 2 , 0
         3814.19  106.21  3944.6          104.75
Permanent Ineff=
       F       F
Bank Sta=3821.34,3944.64
Exp/Cntr=0.5,0.3

Type RM Length L Ch R = 1 ,13799.94,91.4,93.23,90.8
BEGIN DESCRIPTION:
E122-00-S7 (Survey 3855.7 to 3946.89) XS 3
END DESCRIPTION:
XS GIS Cut Line= 6
 3075722.028194813893720.1422122     3073728.962    13892643.951
     3072488.338    13892259.721     3072182.591     13892252.14
     3071958.854    13892246.593     3070003.063    13892214.881
#Sta/Elev= 30
  -19.41  106.24    1.41  102.49  375.54  104.57  994.72  101.29 1110.29  103.47
  1524.7  101.22 1716.49  104.13 1806.81   101.9 2278.14  104.06    2345  101.14
 2516.26  104.62 2636.09  101.34 2762.08  105.26 2909.29  101.48 3045.07  104.83
 3427.03  101.84 3798.97  103.89 3852.72  104.49 3897.86   92.38  3921.9   89.95
 3957.41   94.22 4002.43  104.31 4768.95  102.23 4913.06  104.87 5067.58  102.75
 5260.73  105.31 5337.61  102.81  5416.2  105.54 5937.69  103.25 6030.11  105.38
#Mann= 3 ,-1 , 0
  -19.41     .08       0 3798.97     .04       0 4002.43     .08       0
#XS Ineff= 2 , 0
         3851.42   104.5 4002.58           104.5
Permanent Ineff=
       F       F
Bank Sta=3852.72,4002.43
Exp/Cntr=0.5,0.3

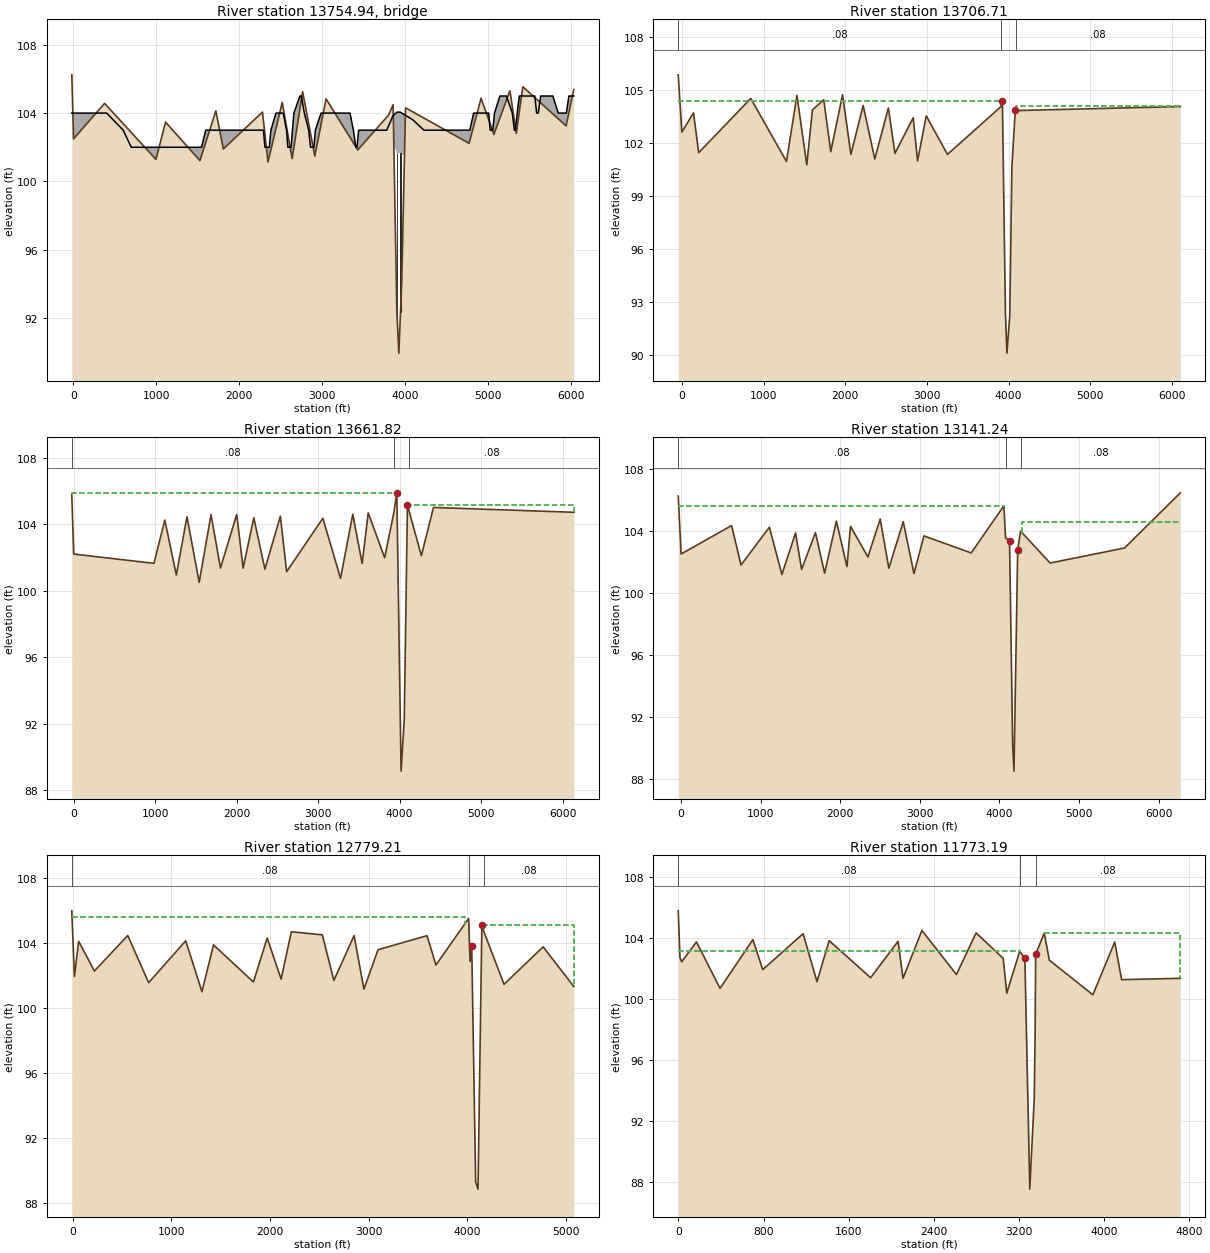
Type RM Length L Ch R = 3 ,13754.94,,,
BEGIN DESCRIPTION:
Structure 7 and 8 - West Road
END DESCRIPTION:
Bridge Culvert--1,0,-1,-1, 0
Deck Dist Width WeirC Skew NumUp NumDn MinLoCord MaxHiCord MaxSubmerge Is_Ogee
0.5,91,2.6,0, 86, 76, , , 0.95, 0, 0,0,,
     -20       0   29.86  177.38  348.32  400.86  599.73  696.53  704.54  748.98
   752.6  869.11 1019.97 1216.47 1288.71 1484.72 1543.95 1594.26 1714.66 1851.19
 2014.14 2123.73 2290.23 2307.65 2360.11 2379.97 2440.68 2528.92 2568.73 2584.18
 2623.08 2639.67 2657.01 2729.96 2746.24 2783.06 2835.62 2857.52 2898.24 2916.17
 2984.77 3333.17  3374.3 3403.95 3417.31  3437.8 3473.71 3775.88 3850.25 3861.29
 3901.32 3941.36 3981.37 4089.27 4224.17 4450.14  4496.9 4724.27 4776.85 4823.37
 4954.28 5005.13 5005.22 5022.86 5053.63 5074.84 5139.79 5156.07 5185.25 5219.46
 5289.39 5314.18 5325.82 5348.24 5373.93  5560.6 5582.37  5602.2 5631.05 5778.02
 5842.99 5879.17 5903.65 5940.47  5971.3    6031
     104     104     104     104     104     104     103     102     102     102
     102     102     102     102     102     102     102     103     103     103
     103     103     103     102     102     103     104     104     103     102
     102     103     104     105     105     104     103     102     102     103
     104     104     103     102     102     103     103     103  103.83   103.9
  104.06  104.05  103.93  103.61     103     103     103     103     103     104
     104     104     104     103     103     104     105     105     105     105
     104     103     103     104     105     105     104     104     105     105
     104     104     104     104     105     105
                                                                                
                                                                                
                                                                                
                                                                                
                                                                  101.43   101.5
  101.66  101.65  101.53  101.21
                                                                                
                                                                                
                                                
     -45       0   95.62  230.84  247.94  270.95  282.51  300.76  420.91  549.44
  647.09  925.62 1566.34 1666.92 1735.59 1925.92 2059.22 2086.97 2112.33 2216.32
 2254.74 2366.45 2452.64 2464.81 2511.67 2549.12 2566.07 2591.26 2619.48 2640.01
  2703.3  2745.4 2771.52  2825.9  2851.5 3105.81 3286.01 3311.74  3725.9 3788.09
 3794.56 3798.14 3801.72  3805.3 3808.87 3812.38 3815.79  3819.2 3822.61  3829.4
 3841.49 3852.15 3863.99 3869.57 3936.62  4056.7 4125.76 4209.27  4629.2 4631.24
 4731.48 4957.13  5088.6 5147.41 5153.92 5188.51 5428.47 5456.23  5497.2 5566.81
 5588.48 5714.63 5749.57 5810.25 5935.85    6102
     104     104     104     104     104     104     104     104     104     103
     102     102     103     103     103     103     103     103     103     103
     102     102     103     103     102     102     103     104     104     104
     104     103     102     102     103     103     103     103     103     103
     102     101     100      99      98      97      96      95      94      93
      92      92      93  103.02   103.7   103.7  103.37     103     103     103
     104     104     104     104     104     104     104     104     104     104
     104     104     104     104     104     104
                                                                                
                                                                                
                                                                                
                                                                                
                                                                                
                          100.72   101.4   101.4  101.07
                                                                                
                                                
Pier Skew, UpSta & Num, DnSta & Num=  ,3902.03, 4 ,3977.32, 4 , 3 , 3 , 0 ,,
     1.5     1.5       2       2
 89.9485   99.75   99.75  101.75
    1.35    1.35       2       2
 90.0842  100.11  100.11  102.11
Pier Skew, UpSta & Num, DnSta & Num=  ,3942.04, 4 ,4016.34, 4 , 3 , 3 , 0 ,,
     1.5     1.5       2       2
 89.9485   99.69   99.69  101.69
    1.35    1.35       2       2
 90.0842  100.15  100.15  102.15
BR Coef=-1 , 1 , 1 ,1.25, 0 ,,,0.8,-1,2,0,
WSPro=,,,, 1 ,,,, 0 ,,,, 0 ,,,,-1 ,-1 ,-1 , 0 , 0 , 0 , 0 , 0
BC Design=,, 0 ,, 0 ,,,,,,
BC HTab HWMax=106.24

Type RM Length L Ch R = 1 ,13706.71,48.18,44.89,41.12
BEGIN DESCRIPTION:
E122-00-S8 (Survey 3935.67 to 4045.74) XS 2
END DESCRIPTION:
XS GIS Cut Line= 6
  3075890.83385513893446.4657934     3073149.188    13892216.988
     3072985.617    13892203.726     3072536.715    13892170.277
      3071937.24    13892155.236     3070011.316    13892082.833
#Sta/Elev= 30
   -44.4  105.88       0  102.63  142.32  103.72  206.06  101.46  843.38  104.54
 1280.73  100.96  1408.3  104.71 1529.16  100.77 1598.18  103.89 1736.76  104.46
 1822.85  101.52 1967.07  104.75  2068.9  101.36 2219.32  104.14 2361.71   101.1
 2528.18     104  2608.2  101.42  2831.7  103.44 2885.42  100.99 2991.39  103.55
 3251.26  101.36 3904.96  104.07 3923.52  104.41 3960.69   92.39 3979.05   90.08
 4013.72    92.2 4039.74  100.64 4080.97  103.87 4088.01  103.85  6101.5  104.08
#Mann= 3 ,-1 , 0
   -44.4     .08       0 3904.96     .04       0 4088.01     .08       0
#XS Ineff= 2 , 0
          3923.2  104.42 4084.84          104.11
Permanent Ineff=
       F       F
Bank Sta=3923.52,4080.97
Exp/Cntr=0.5,0.3

Type RM Length L Ch R = 1 ,13661.82,504.11,520.58,519.26
BEGIN DESCRIPTION:
E122-00-SV8 (Survey 3938.67 to 4115.72) XS 1
END DESCRIPTION:
XS GIS Cut Line= 6
 3075900.701224713893383.9902531     3073149.188    13892146.255
     3072601.643     13892103.97     3072216.743    13892113.217
     3071924.015    13892120.249     3070011.316    13892049.821
#Sta/Elev= 30
  -21.31  105.82    2.29  102.21  986.79  101.65 1119.84  104.25 1260.94  100.95
 1391.69  104.45 1541.49  100.51 1686.82  104.58 1802.48  101.37 2002.03  104.59
 2080.19  101.36 2211.22  104.39 2347.43   101.3 2537.25  104.48 2613.97  101.15
 3058.55  104.36 3275.33  100.75 3425.27   104.6 3540.25  101.64 3615.02  104.68
 3816.21  101.99 3927.53  104.66 3965.62  105.89 4017.68   89.16 4056.81   92.25
 4095.77  105.16 4115.72   104.8 4266.35  102.11 4415.26  105.01 6136.77  104.72
#Mann= 3 ,-1 , 0
  -21.31     .08       0 3927.53     .04       0 4115.72     .08       0
#XS Ineff= 2 , 0
          3964.4  105.89 4095.57          105.16
Permanent Ineff=
       F       F
Bank Sta=3965.62,4095.77
Exp/Cntr=0.3,0.1

Type RM Length L Ch R = 1 ,13141.24,238.64,362.03,450.11
BEGIN DESCRIPTION:
E122-00-V7 (Survey 4056.03 to 4247.87)
END DESCRIPTION:
XS GIS Cut Line= 6
 3076003.745643113893212.7881513     3073290.739    13891990.662
     3072465.284    13891682.996     3072348.739    13891624.557
     3072034.984    13891595.726     3070035.877    13891412.024
#Sta/Elev= 30
  -36.02  106.27       0  102.53  634.28  104.37  753.06  101.82 1109.45  104.26
 1266.71  101.21 1438.06  103.89 1514.22  101.54 1688.33  103.91 1803.46   101.3
 1951.66  104.65 2084.36  101.72 2128.76  104.32 2347.59  102.34 2501.97  104.79
 2610.81  101.61 2791.78  104.62 2926.39  101.27  3051.9   103.7 3645.46   102.6
 4056.03  105.64 4077.75  103.57 4127.37   103.4 4166.57   90.18  4183.5   88.52
 4229.76  102.76 4265.95  104.01 4637.35  101.95 5572.69  102.92 6273.46  106.48
#Mann= 3 ,-1 , 0
  -36.02     .08       0 4077.75     .04       0 4265.95     .08       0
#XS Ineff= 2 , 0
         4054.99  105.64 4284.55           104.6
Permanent Ineff=
       F       F
Bank Sta=4127.37,4229.76
Exp/Cntr=0.3,0.1

Type RM Length L Ch R = 1 ,12779.21,1003.79,1006.01,1006.96
BEGIN DESCRIPTION:
E122-00-V8 (Survey 4016.28 to 4163.33)
END DESCRIPTION:
XS GIS Cut Line= 6
 3076039.805073113893128.1267565     3073307.567    13891948.201
     3072397.984    13891610.348      3072399.08    13891540.735
     3072404.869    13891371.711     3072435.891    13890465.851
#Sta/Elev= 30
  -10.53     106   16.38  101.95   59.55  104.12  219.13  102.29  557.49  104.48
  768.87  101.57 1145.12  104.15  1309.9  101.01 1426.56   103.9 1831.76  101.61
 1971.21  104.32 2112.62  101.79  2216.3  104.71 2530.33  104.52 2647.49  101.71
 2852.43  104.47  2952.3  101.17  3095.2   103.6 3591.89  104.47 3682.72  102.66
 4014.02  105.53 4028.28  102.88 4045.27  103.85 4085.31   89.29 4109.33   88.84
 4148.38  105.13 4166.45  104.75 4373.18  101.47 4769.74  103.78 5081.04  101.33
#Mann= 3 ,-1 , 0
  -10.53     .08       0 4014.02     .04       0 4166.45     .08       0
#XS Ineff= 2 , 0
         3974.16   105.6 4148.45          105.14
Permanent Ineff=
       F       F
Bank Sta=4045.27,4148.38
Exp/Cntr=0.3,0.1

Type RM Length L Ch R = 1 ,11773.19,998.46,1001.13,1002.61
BEGIN DESCRIPTION:
E122-00-V9 (Survey 3227.74 to 3378.01)
END DESCRIPTION:
XS GIS Cut Line= 6
 3076095.641553513893022.8577241     3073386.501    13891844.962
     3073401.647    13891581.254     3073411.487    13891409.915
     3073417.221     13891310.08     3072516.137    13890475.364
#Sta/Elev= 30
   -1.79  105.79   14.54  102.72   31.12  102.45  169.55  103.75  390.96   100.7
  699.97   103.9  792.25  101.93 1171.77  104.29 1302.01  101.14 1416.59  103.83
 1806.17   101.4 2064.19  103.79  2110.5  101.36 2288.31   104.5 2612.59  101.61
 2797.41  104.34 3051.81  102.67 3085.78  100.39 3207.15  103.13 3255.75  102.67
 3301.85   87.52 3343.95    93.5 3351.93    97.7 3356.98  102.93 3437.65  104.33
 3485.86  102.55 3894.54  100.28 4100.27  103.74 4164.74  101.27  4716.4  101.36
#Mann= 3 ,-1 , 0
   -1.79     .08       0 3207.15     .04       0 3356.98     .08       0
#XS Ineff= 2 , 0
         3208.63  103.15 3437.75          104.34
Permanent Ineff=
       F       F
Bank Sta=3255.75,3356.98
Exp/Cntr=0.3,0.1

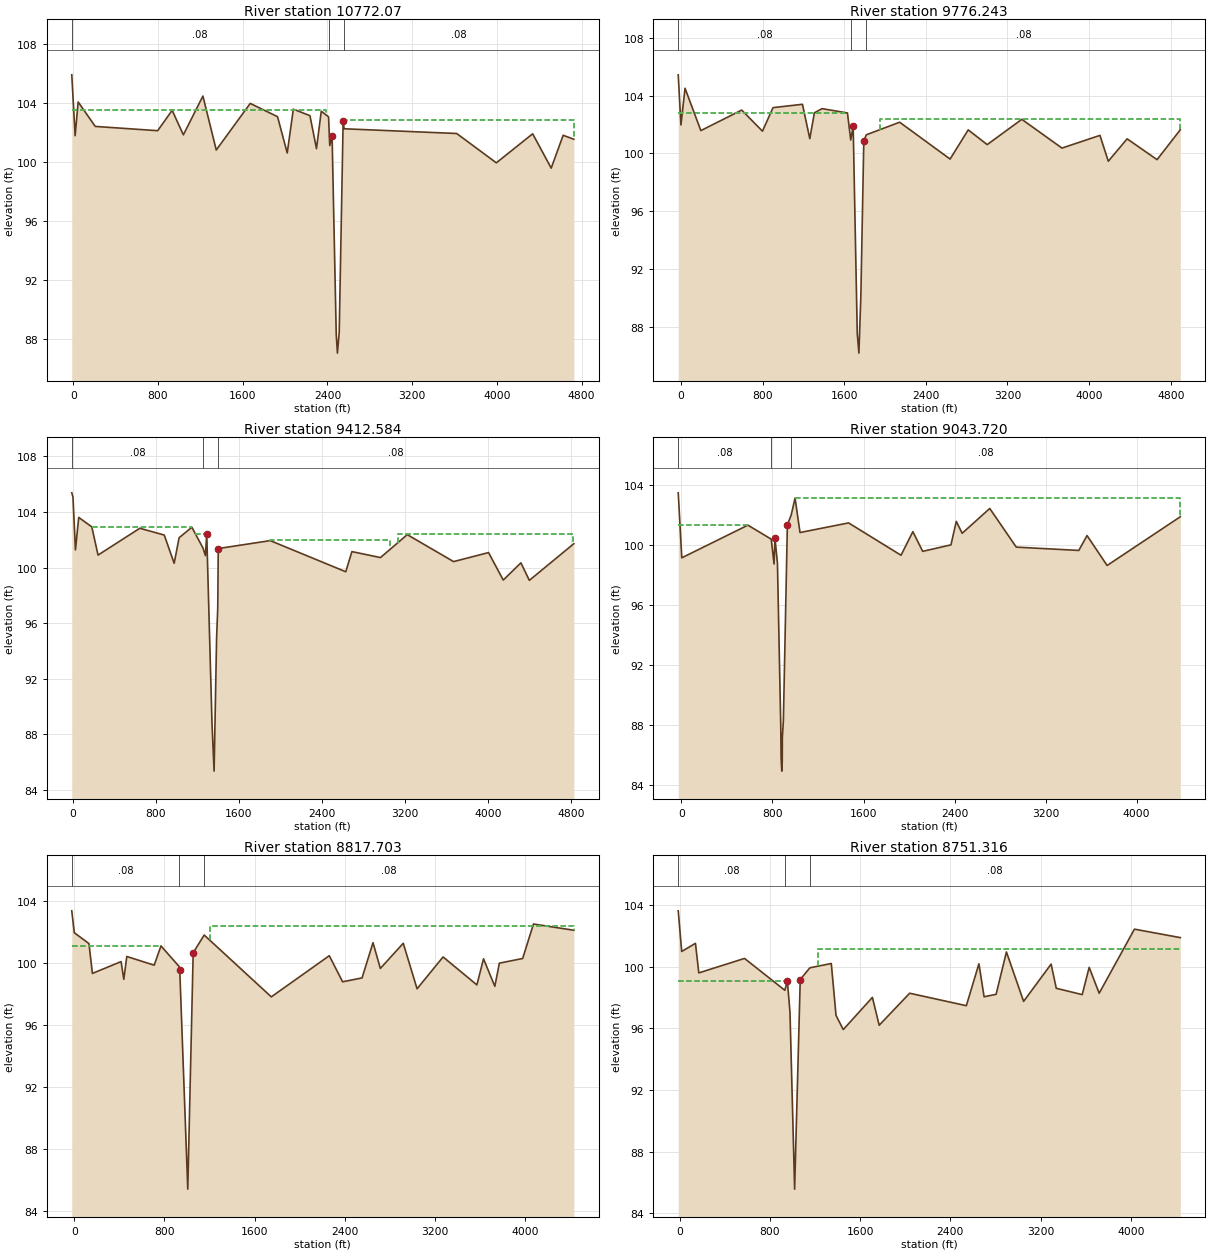
Type RM Length L Ch R = 1 ,10772.07,997.66,995.83,994.14
BEGIN DESCRIPTION:
E122-00-V10 (Survey 2414.58 to 2563.15)
END DESCRIPTION:
XS GIS Cut Line= 6
 3076162.103207213892898.5454505     3074362.304    13892043.118
     3074390.385    13891718.507     3074413.474    13891451.592
     3074422.093    13891351.964      3072563.69    13890478.336
#Sta/Elev= 30
  -13.92   105.9    17.9  101.77    46.5  104.06  207.84   102.4  796.98  102.11
  933.75  103.49 1039.74  101.83 1224.21  104.46 1350.21   100.8 1670.84  103.96
 1928.71  103.06 2020.16   100.6 2077.89  103.57 2234.68  103.13 2296.39  100.89
 2341.55  103.43 2410.29  103.05 2421.72   101.1 2443.73  101.75 2482.93   88.29
 2493.97   87.02 2511.08   88.45  2548.2   102.8 2557.17  102.24 3619.96  101.92
 3994.43   99.93 4337.36   101.9 4512.34   99.57  4625.2   101.8 4726.07  101.53
#Mann= 3 ,-1 , 0
  -13.92     .08       0 2410.29     .04       0 2557.17     .08       0
#XS Ineff= 2 , 0
         2389.42  103.51 2548.87          102.81
Permanent Ineff=
       F       F
Bank Sta=2443.73,2548.2
Exp/Cntr=0.3,0.1

Type RM Length L Ch R = 1 ,9776.243,369.56,363.66,358.39
BEGIN DESCRIPTION:
E122-00-V11 (Survey 1658.98 to 1817.29)
END DESCRIPTION:
XS GIS Cut Line= 6
 3076210.503846813892802.1935652     3075372.087     13892402.04
     3075390.269    13891754.004      3075396.36    13891654.189
     3075412.869    13891383.615     3072584.495     13890469.42
#Sta/Elev= 30
  -26.54  105.44       0  101.97   40.07  104.51  195.11  101.58  595.47     103
  799.01  101.54  902.47  103.17  1191.1   103.4 1262.92  101.02 1307.74  102.81
 1383.12   103.1 1632.15   102.8 1664.06  100.93 1688.05  101.89 1728.15   87.52
 1744.25   86.18 1763.21   90.11 1792.28  100.89 1817.29  101.29 2143.74  102.16
 2637.98   99.61 2815.58  101.63 3001.58  100.61 3340.86  102.36 3734.32  100.37
 4106.78  101.25 4188.52   99.46 4373.06  101.01 4666.53   99.57 4894.29  101.64
#Mann= 3 ,-1 , 0
  -26.54     .08       0 1664.06     .04       0 1817.29     .08       0
#XS Ineff= 2 , 0
         1632.23   102.8 1947.27           102.4
Permanent Ineff=
       F       F
Bank Sta=1688.05,1792.28
Exp/Cntr=0.3,0.1

Type RM Length L Ch R = 1 ,9412.584,473.27,368.86,261.83
BEGIN DESCRIPTION:
E122-00-V12 (Survey 1270.27 to 1419.34)
END DESCRIPTION:
XS GIS Cut Line= 6
 3076361.360804213892540.9447878     3075780.539    13892314.704
     3075769.442    13891770.955     3075763.929    13891500.794
     3075761.888    13891400.815     3072600.129     13890458.43
#Sta/Elev= 30
   -8.86  105.38    2.83  105.07   26.57  101.27   58.19  103.61  184.22  102.93
   244.3   100.9  646.85  102.83   882.1  102.34  977.51  100.31 1025.29  102.15
 1147.95   102.9 1255.22  101.41 1278.29  100.86 1291.29  102.42 1342.28   88.72
 1362.29   85.35 1386.31   94.94 1397.49   97.11 1402.31  101.37 1902.75  101.94
 2630.74    99.7 2689.83  101.15 2964.81  100.72 3223.26  102.37 3669.23  100.43
 4006.36  101.08 4147.73    99.1 4317.76  100.34 4399.21   99.08 4827.76  101.72
#Mann= 3 ,-1 , 0
   -8.86     .08       0 1255.22     .04       0 1402.31     .08       0
#XS Ineff= 6 ,-1
  185.42 1146.58  102.91 1177.16 1290.76  102.42  1456.6 1634.77  101.39
 1666.74 1889.55  101.57 1902.66 3060.42  101.95 3129.36 4822.37  102.43
Permanent Ineff=
       F       F       F       F       F       F
Bank Sta=1291.29,1402.31
Exp/Cntr=0.3,0.1

Type RM Length L Ch R = 1 ,9043.720,224.98,226.02,227.14
BEGIN DESCRIPTION:
E122-00-V13 (Survey 813.61 to 970.77)
END DESCRIPTION:
XS GIS Cut Line= 6
  3076890.90661513891530.5605398     3076178.161    13891356.674
     3076078.244    13891352.609     3075907.483    13891345.663
     3075807.566    13891341.598     3072627.895    13890430.664
#Sta/Elev= 30
   -28.3  103.45    3.03   99.13  583.94   101.3  789.09  100.37  813.61   98.72
  821.61  100.44  843.63   98.77  872.73   87.93  875.68   85.81  881.76   84.95
  885.76   85.62  886.76   87.21  895.71    88.3  930.76  101.31  964.44  101.98
  998.29   103.1 1041.87  100.81 1468.82  101.45 1929.63    99.3 2033.62  100.87
 2119.93   99.56 2368.32   99.99 2415.13  101.55 2466.86  100.76 2709.28  102.41
 2942.33   99.84 3491.77   99.62 3564.22  100.61 3740.63   98.62 4383.84  101.86
#Mann= 3 ,-1 , 0
   -28.3     .08       0  789.09     .04       0  964.44     .08       0
#XS Ineff= 2 , 0
          584.15  101.31  998.52          103.11
Permanent Ineff=
       F       F
Bank Sta=821.61,930.76
Exp/Cntr=0.3,0.1

Type RM Length L Ch R = 1 ,8817.703,55.01,66.39,80.7
BEGIN DESCRIPTION:
E122-00-SV9 (Survey 936.32 to 1055.41) XS 4
END DESCRIPTION:
XS GIS Cut Line= 6
 3077025.522869413891269.3030915     3076360.297    13891144.145
     3076193.703    13891134.421     3075732.261    13891107.489
      3073356.78     13890607.74     3072667.481    13890386.811
#Sta/Elev= 30
  -22.51  103.35       0  101.94  130.18  101.24  160.71   99.32   415.2  100.08
  439.56   98.94  465.97  100.41  709.31   99.85  769.41  101.09  931.31   99.76
  936.32   99.53 1007.38   85.43 1055.41  100.65 1153.05  101.79 1749.12   97.81
 2263.68  100.46 2382.02   98.78 2554.55   99.03 2651.86   101.3 2717.04   99.64
 2920.35  101.26 3042.98   98.33 3273.94  100.38 3573.96   98.58 3632.97  100.26
 3733.36   98.49 3773.71   99.98 3980.31  100.28 4076.45   102.5 4434.81   102.1
#Mann= 3 ,-1 , 0
  -22.51     .08       0  931.31     .04       0 1153.05     .08       0
#XS Ineff= 2 , 0
          768.39  101.11  1205.2          102.37
Permanent Ineff=
       F       F
Bank Sta=936.32,1055.41
Exp/Cntr=0.5,0.3

Type RM Length L Ch R = 1 ,8751.316,45.44,44.36,43.04
BEGIN DESCRIPTION:
E122-00-S9 (Survey 977.93 to 1068.79) XS 3
END DESCRIPTION:
XS GIS Cut Line= 6
 3077025.627359513891249.6226134     3076174.831    13891091.838
        3075819.    13891025.848     3075243.629    13890934.322
     3073392.835    13890600.082     3072669.478    13890360.626
#Sta/Elev= 30
  -13.22  103.64   17.46     101   139.5  101.53  169.23   99.61  574.64  100.55
  932.25   98.48  954.58   99.08  977.93   97.04 1018.97   85.57 1068.79   99.18
 1154.21   99.94 1344.13  100.22 1386.12   96.85 1450.45   95.93 1708.66   98.02
 1768.87   96.21 2039.13   98.29 2541.69   97.48 2653.39   100.2 2699.12   98.06
 2805.82   98.22 2897.27  100.97  3049.7   97.76 3293.58  100.18 3339.31   98.61
 3569.24    98.2 3631.14   99.97 3719.78   98.29 4032.69  102.45 4439.28   101.9
#Mann= 3 ,-1 , 0
  -13.22     .08       0  932.25     .04       0 1154.21     .08       0
#XS Ineff= 2 , 0
          953.37   99.08 1223.84          101.16
Permanent Ineff=
       F       F
Bank Sta=954.58,1068.79
Exp/Cntr=0.5,0.3