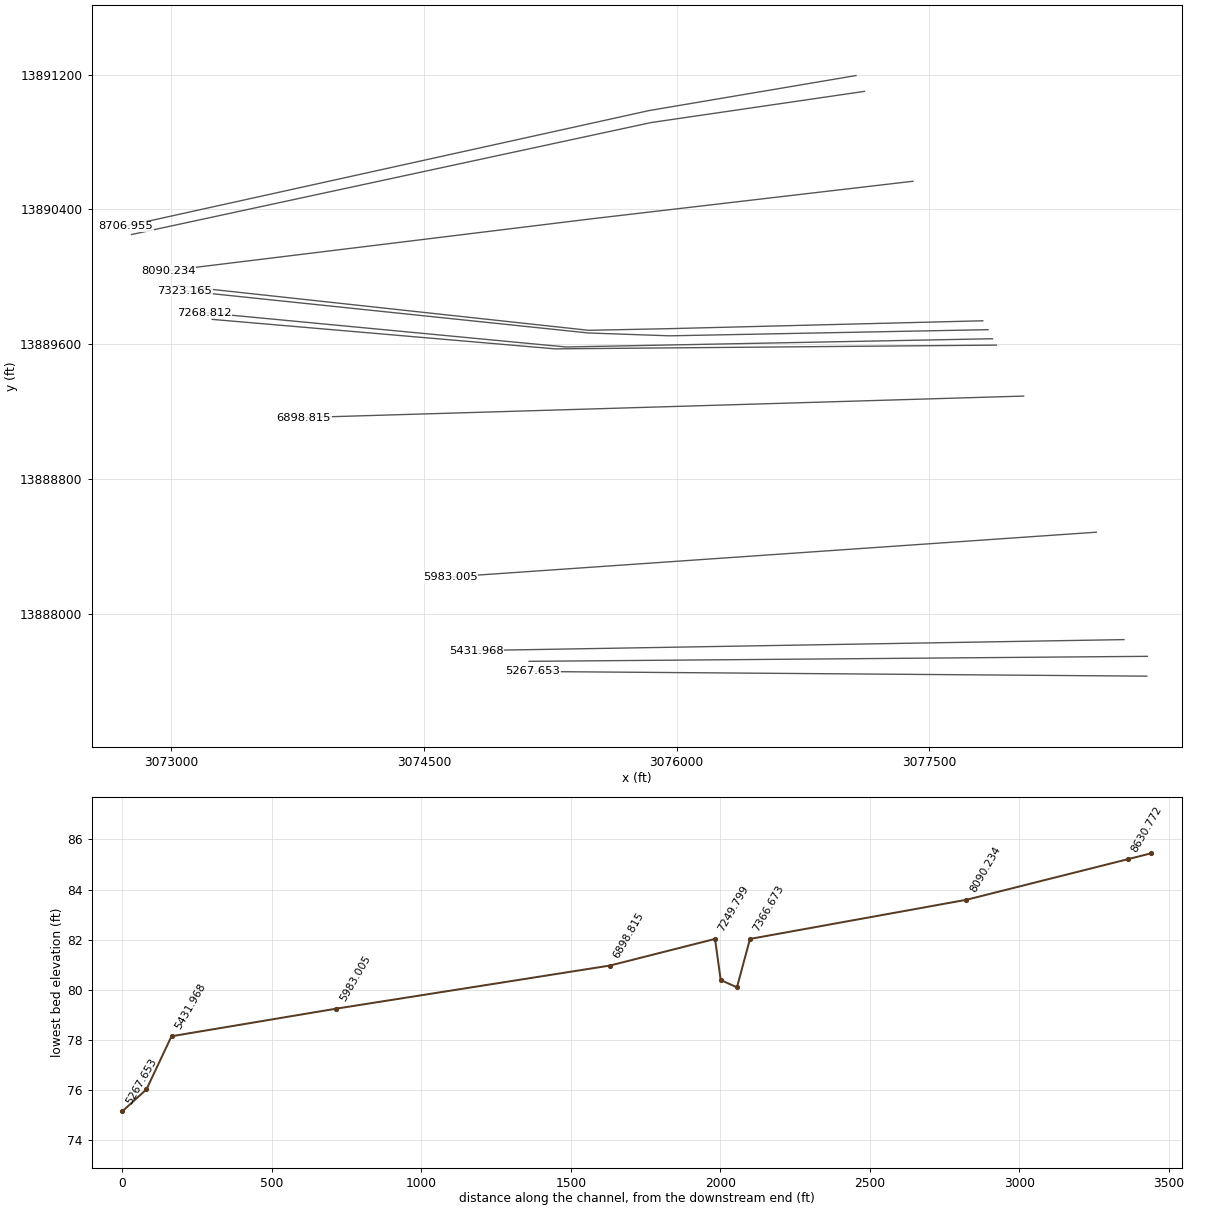
HEC-RAS study E122-00-00.prj: E122-00-00

--- E122-00-00.g08 (geometry) --- (continued)

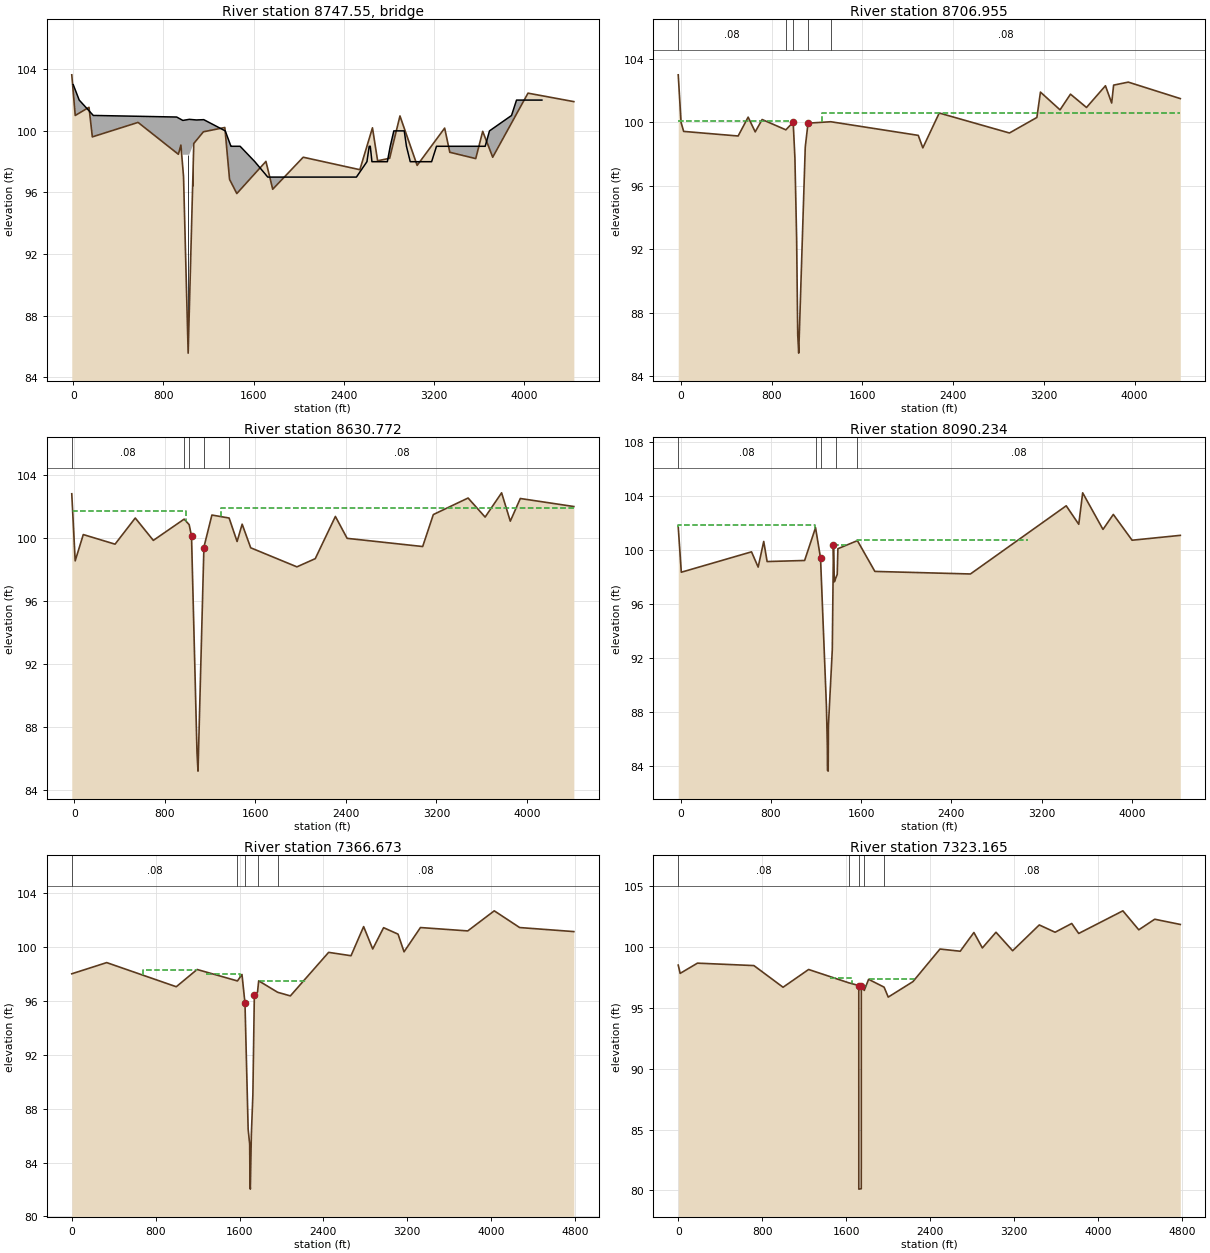
Type RM Length L Ch R = 3 ,8747.55 ,,,
BEGIN DESCRIPTION:
Structure 9 - Breen Road
END DESCRIPTION:
Bridge Culvert--1,0,-1,-1, 0
Deck Dist Width WeirC Skew NumUp NumDn MinLoCord MaxHiCord MaxSubmerge Is_Ogee
3.76,37.1,2.6,0, 61, 62, 100.6792, , 0.95, 0, 0,0,,
       0   52.86  178.11  188.99  207.53   916.9  971.98 1028.86    1092  1157.1
 1347.95  1398.3 1400.49 1441.54 1476.68 1479.87 1610.42 1724.86 1991.64 2017.15
 2132.61 2140.27 2165.99 2226.68 2272.28 2288.84 2317.82 2342.42 2363.08  2483.6
 2511.02 2604.36 2624.42 2634.14 2648.71 2785.42 2810.96 2842.86 2935.25 2954.77
 2988.53  3001.6 3015.56 3056.27 3098.16 3111.53  3136.8    3178 3221.29 3287.04
 3367.54 3386.21 3462.69 3481.78 3525.78 3580.61 3653.07 3691.12  3886.5 3930.95
 4155.81
     103     102     101     101     101   100.9  100.68  100.75  100.71  100.73
     100      99      99      99      99      99      98      97      97      97
      97      97      97      97      97      97      97      97      97      97
      97      98      99      99      98      98      99     100     100      99
      98      98      98      98      98      98      98      98      99      99
      99      99      99      99      99      99      99     100     101     102
     102
                                           98.45   98.45   98.45   98.45   98.45
                                                                                
                                                                                
                                                                                
                                                                                
                                                                                
        
     -25   19.13   71.99  197.24  208.12  226.66  936.03  991.11 1047.99 1111.13
 1176.23 1367.08 1417.43 1419.62 1460.67 1495.81    1499 1629.55 1743.99 2010.77
 2036.28 2151.74  2159.4 2185.12 2245.81 2291.41 2307.97 2336.95 2361.55 2382.21
 2502.73 2530.15 2623.49 2643.55 2653.27 2667.84 2804.55 2830.09 2861.99 2954.38
  2973.9 3007.66 3020.73 3034.69  3075.4 3117.29 3130.66 3155.93 3197.13 3240.42
 3306.17 3386.67 3405.34 3481.82 3500.91 3544.91 3599.74  3672.2 3710.25 3905.63
 3950.08 4174.94
     103     103     102     101     101     101     101     101     101     101
     101     100      99      99      99      99      99      98      97      97
      97      97      97      97      97      97      97      97      97      97
      97      97      98      99      99      98      98      99     100     100
      99      98      98      98      98      98      98      98      98      99
      99      99      99      99      99      99      99      99     100     101
     102     102
                                                   98.45   98.45   98.45   98.45
   98.45
                                                                                
                                                                                
                                                                                
                                                                                
                
Pier Skew, UpSta & Num, DnSta & Num=  ,1016.5, 4 ,1016.5, 4 , 3 , 3 , 0 ,,
    1.35    1.35       2       2
 85.5686   95.95   95.95   98.45
    1.35    1.35       2       2
   85.25   95.95   95.95   98.45
Pier Skew, UpSta & Num, DnSta & Num=  ,1058.77, 4 ,1058.77, 4 , 3 , 3 , 0 ,,
    1.35    1.35       2       2
 85.5686  95.957  95.957  98.457
    1.35    1.35       2       2
 85.2476  95.957  95.957  98.457
BR Coef=-1 , 1 , 1 ,1.25, 0 ,,,0.8,-1,2,0,
WSPro=,,,, 1 ,,,, 0 ,,,, 0 ,,,,-1 ,-1 ,-1 , 0 , 0 , 0 , 0 , 0
BC Design=,, 0 ,, 0 ,,,,,,
BC HTab HWMax=103.64

Type RM Length L Ch R = 1 ,8706.955,77.64,76.18,75.28
BEGIN DESCRIPTION:
Survey 1029.4 to 1038.1 from S9 XS 2
END DESCRIPTION:
XS GIS Cut Line= 6
 3077065.0352328 13891194.709689     3076178.491    13891044.679
     3076079.893    13891027.994      3075935.29    13891003.522
     3075836.691    13890986.836     3072729.342    13890300.762
#Sta/Elev= 30
  -24.45     103     .47     100   23.33   99.43  503.82   99.14  592.13  100.33
  654.43    99.4  715.49  100.18  924.74   99.53  989.33  100.01 1004.55   97.76
 1019.76   92.66  1029.4    86.6  1038.1   85.44 1095.83   98.44 1120.14   99.95
 1321.06  100.04  2092.5   99.18 2132.64   98.39 2277.42  100.59 2896.67   99.33
 3138.55  100.31  3170.1  101.91 3342.88  100.79 3435.02  101.78 3576.11  100.94
 3743.27  102.31 3798.19  101.22 3815.43  102.35  3944.6  102.54 4403.55   101.5
#Mann= 5 ,-1 , 0
  -24.45     .08       0  924.74     .06       0  989.33     .08       0
 1120.14     .06       0 1321.06     .08       0
#XS Ineff= 2 , 0
          988.65  100.09 1242.79          100.62
Permanent Ineff=
       F       F
Bank Sta=989.33,1120.14
Exp/Cntr=0.5,0.3

Type RM Length L Ch R = 1 ,8630.772,535.79,540.54,529.77
BEGIN DESCRIPTION:
Survey 1084.66 to 1093.42 (1029.4 to 1038.1 from S9) XS 1
END DESCRIPTION:
XS GIS Cut Line= 6
 3077115.487725313891100.8101042     3076191.077    13890965.704
     3076092.128    13890951.243     3075947.525    13890930.108
     3075848.576    13890915.647     3072764.263    13890250.875
#Sta/Elev= 30
  -21.81  102.82    8.38   98.56   79.92  100.23  360.52   99.62  539.11  101.28
  698.72   99.86  971.01  101.21 1015.15  100.86 1036.09  100.14 1084.66   86.37
 1093.42   85.21 1145.34   99.36 1147.56   99.49 1216.19  101.47 1368.25  101.28
 1438.74   99.79 1483.46  100.89 1558.91   99.39 1967.08   98.18 2129.25    98.7
 2307.19  101.38 2410.77   99.99 3078.28   99.47 3172.36   101.5 3479.46  102.55
  3629.9  101.34 3775.45  102.88 3852.44  101.08 3940.68  102.52  4413.7  102.01
#Mann= 5 ,-1 , 0
  -21.81     .08       0  971.01     .06       0 1015.15     .08       0
 1147.56     .06       0 1368.25     .08       0
#XS Ineff= 2 , 0
           991.2   101.7 1297.36          101.91
Permanent Ineff=
       F       F
Bank Sta=1036.09,1145.34
Exp/Cntr=0.3,0.1

Type RM Length L Ch R = 1 ,8090.234,725.17,723.56,711.4
BEGIN DESCRIPTION:
E122-00-V14 (Survey 1227.14 to 1394.35)
END DESCRIPTION:
XS GIS Cut Line= 6
  3077403.22419513890567.1258819     3076174.911    13890423.557
     3075996.626    13890402.718     3075897.302    13890391.109
     3075492.508    13890343.795     3072983.764    13890036.362
#Sta/Elev= 30
  -21.12  101.66    6.13   98.32  628.52   99.83  687.47    98.7  736.76   100.6
  766.97   99.11 1099.42   99.19 1196.13  101.62  1240.4   99.38 1292.94   88.35
 1300.89   85.38 1301.99   83.65  1308.3   83.59  1310.4   86.97 1344.76   92.59
 1354.92  100.33 1362.98   97.61 1373.34   97.84 1388.39   98.16 1394.35  100.06
 1567.38  100.66 1722.18   98.38 2569.36   98.19 3418.57  103.24 3529.77  101.87
 3564.45   104.2 3744.66  101.49 3836.26   102.6 4002.66  100.69 4430.11  101.05
#Mann= 5 ,-1 , 0
  -21.12     .08       0 1196.13     .06       0  1240.4     .08       0
 1373.34     .06       0 1567.38     .08       0
#XS Ineff= 3 ,-1
  -21.12 1189.71  101.79    1355 1472.41  100.33 1567.14 3076.19  100.67
Permanent Ineff=
       F       F       F
Bank Sta=1240.4,1354.92
Exp/Cntr=0.3,0.1

Type RM Length L Ch R = 1 ,7366.673,43.95,43.51,43.3
BEGIN DESCRIPTION:
E122-00-SV10 (Survey 1682.58 to 1754.59) XS 4
END DESCRIPTION:
XS GIS Cut Line= 6
     3077818.016    13889738.712     3076283.563     13889700.19
     3076045.249    13889694.207     3075945.281    13889691.697
     3075478.096    13889682.167     3073043.628    13889946.567
#Sta/Elev= 30
       0      98  333.13   98.83  996.89   97.04  1195.6   98.32  1580.5   97.47
 1623.67   97.95 1652.34   95.83 1682.58   86.47  1697.1   85.36 1700.13   82.47
 1703.28   82.03  1713.1   86.08 1727.59   89.03 1741.61   96.43 1772.07   96.65
 1783.11   97.48 1963.65   96.63 2085.15   96.36 2450.32   99.59 2663.84   99.34
 2784.17   101.5 2870.88   99.84 2974.53  101.42 3112.43  100.94 3169.72   99.63
 3326.13  101.43 3777.31  101.18 4030.26  102.67 4272.48  101.43 4789.39  101.13
#Mann= 5 ,-1 , 0
       0     .08       0  1580.5     .06       0 1652.34     .08       0
 1772.07     .06       0 1963.65     .08       0
#XS Ineff= 3 ,-1
  684.11 1193.81   98.31 1284.83 1605.22   98.01 1783.62 2235.08   97.48
Permanent Ineff=
       F       F       F
#Block Obstruct= 2 , 0
          183.81   98.83
Bank Sta=1652.34,1741.61
Exp/Cntr=0.5,0.3

Type RM Length L Ch R = 1 ,7323.165,54.41,54.35,54.3
BEGIN DESCRIPTION:
E122-00-S10 (Survey 1720.64 to 1785.49) XS 3
Data inserted from bridge survey
END DESCRIPTION:
XS GIS Cut Line= 6
     3077849.309    13889685.976     3076178.385    13889653.688
     3076058.563    13889651.372     3075958.582     13889649.44
     3075476.232    13889666.352     3073078.549    13889916.635
#Sta/Elev= 30
       0   98.51   18.47   97.83  183.15   98.67  721.08   98.47  998.97   96.69
 1242.33   98.15 1626.71   97.05 1720.64   96.83 1720.73    80.1 1744.23   80.13
 1744.64   96.82 1772.51   96.43 1814.18   97.34 1961.62    96.7  2001.2   95.88
 2236.33   97.15 2494.21   99.83 2687.11   99.65 2817.59  101.19 2898.14   99.92
 3027.96  101.21 3186.55   99.69 3440.38  101.81 3591.07  101.21 3749.77  101.93
 3816.16  101.11 4237.23  102.97 4388.62  101.41 4540.49  102.28 4784.44  101.85
#Mann= 5 ,-1 , 0
       0     .08       0 1626.71     .06       0 1720.64     .08       0
 1772.51     .06       0 1961.62     .08       0
#XS Ineff= 4 ,-1
  735.76 1241.82   98.14 1443.43 1657.37   97.45 1744.79 1800.01   96.82
 1814.49 2246.79   97.34
Permanent Ineff=
       F       F       F       F
#Block Obstruct= 2 , 0
          213.32   98.68
Bank Sta=1720.64,1744.64
Exp/Cntr=0.5,0.3

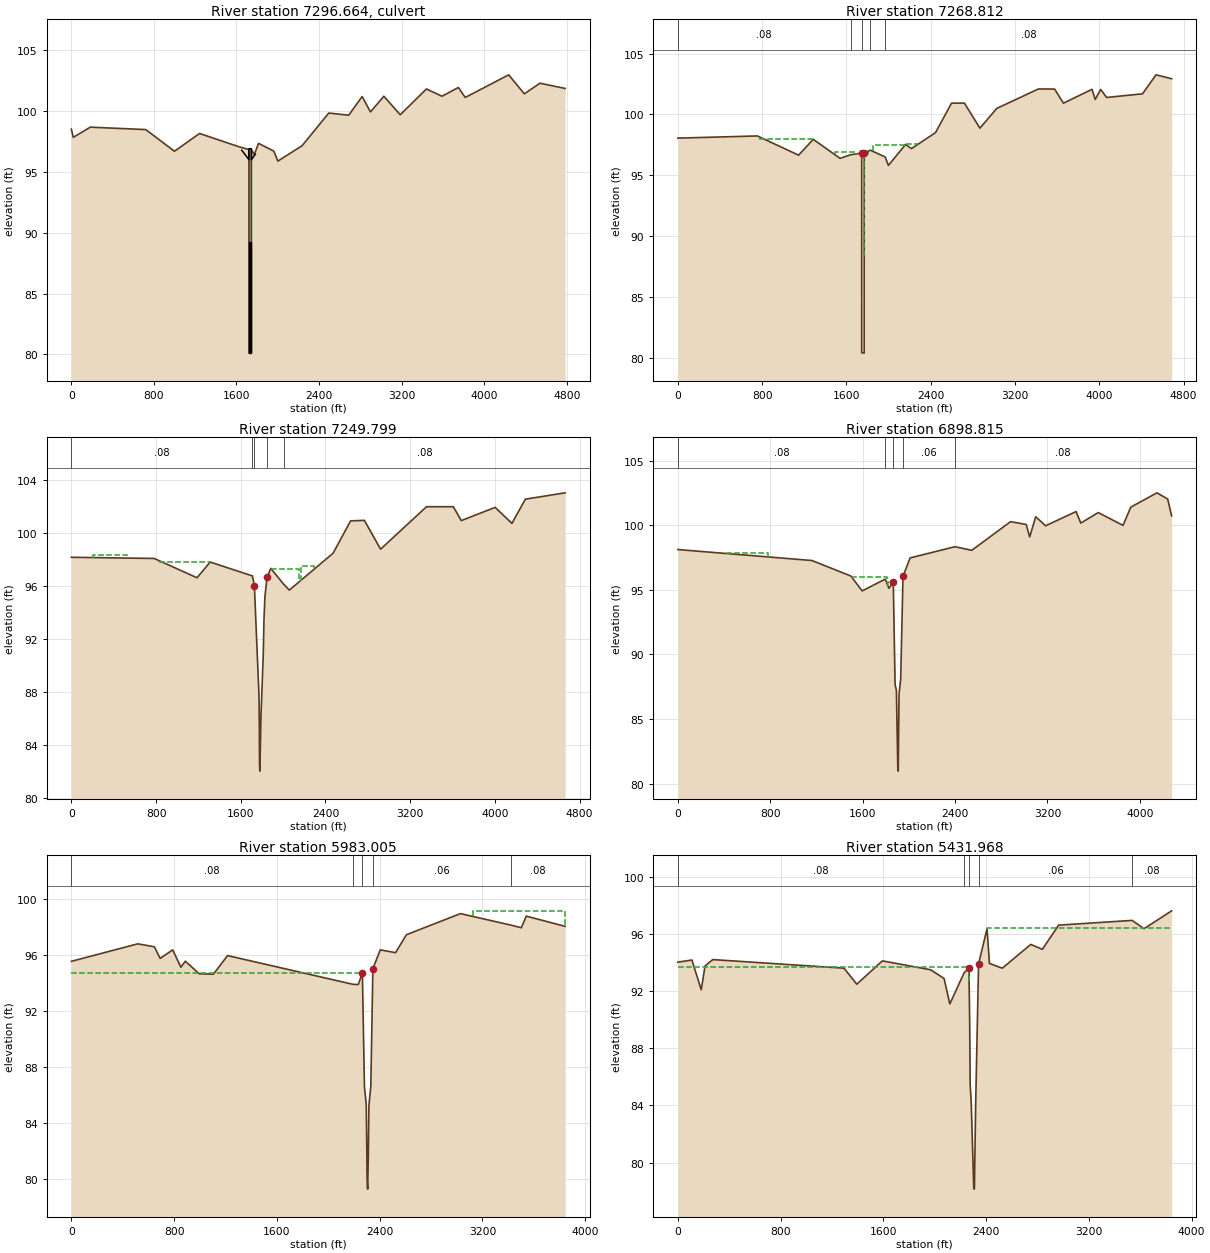
Type RM Length L Ch R = 2 ,7296.664,,,
BEGIN DESCRIPTION:
Structure 10
END DESCRIPTION:
Bridge Culvert--1,0,-1,-1, 0
Deck Dist Width WeirC Skew NumUp NumDn MinLoCord MaxHiCord MaxSubmerge Is_Ogee
0.5,50,2.6,0, 6, 6, 96, , 0.95, 0, 0,0,,
 1651.12 1720.53 1720.53 1744.52 1744.52 1783.12
   96.77      96    96.9    96.9      96   96.45
      75      75      75      75      75      75
 1676.25 1745.66 1745.66 1769.65 1769.65 1808.25
   96.77      96    96.9    96.9      96   96.45
      75      75      75      75      75      75
BR Coef=-1 , 0 , 0 ,, 0 ,,,0.8,-1,,1,
WSPro=,,,, 1 ,,,, 0 ,,,, 0 ,,,,-1 ,-1 ,-1 , 0 , 0 , 0 , 0 , 0
Multiple Barrel Culv=2,9.1,11,50,0.013,0.4,1,8,1,80.1,80.4, 2,Culvert #1  , 0 ,0.5
 1726.63 1751.76 1738.43 1763.56
Culvert Bottom n=0.013
BC Design=,, 0 ,, 0 ,,,,,,
BC HTab HWMax=102.97

Type RM Length L Ch R = 1 ,7268.812,19.6,19.01,18.45
BEGIN DESCRIPTION:
Survey 1745.38 to 1810.23 XS 2
Data inserted from bridge survey
END DESCRIPTION:
XS GIS Cut Line= 6
     3077875.405    13889632.118       3076179.8    13889599.353
     3076059.978    13889597.038     3075959.996    13889595.106
     3075343.483    13889583.192     3073198.277    13889786.929
#Sta/Elev= 30
       0   98.05  754.97   98.23 1146.33   96.65 1285.55   97.95 1540.23   96.39
 1640.54   96.68 1745.38   96.83 1745.47   80.42 1768.97   80.39 1769.38   96.82
 1828.03   97.06 1968.65    96.5 1998.67   95.81 2161.83   97.53 2218.18   97.19
 2445.93    98.5 2598.05  100.92 2719.97  100.93 2867.65   98.87 3027.63  100.49
 3423.42  102.09 3576.69  102.08 3660.47  100.92 3931.68  102.06 3961.82  101.23
 4013.54  102.05 4070.43  101.39 4411.19  101.69 4539.35  103.25 4687.25  102.93
#Mann= 5 ,-1 , 0
       0     .08       0 1640.54     .06       0 1745.38     .08       0
 1828.03     .06       0 1968.65     .08       0
#XS Ineff= 5 ,-1
  769.02 1279.62   97.95 1488.29 1688.09   96.89 1769.17 1810.59   96.82
 1850.27 2154.71   97.45 2162.25 2277.99   97.54
Permanent Ineff=
       F       F       F       F       F
#Block Obstruct= 2 , 0
          166.29    98.5
Bank Sta=1745.38,1769.38
Exp/Cntr=0.5,0.3

Type RM Length L Ch R = 1 ,7249.799,345.63,350.98,346.3
BEGIN DESCRIPTION:
Survey 1777.29 to 1790.34  XS 1
END DESCRIPTION:
XS GIS Cut Line= 6
     3077898.837    13889594.237     3076287.785    13889580.584
     3076056.534    13889578.625     3075956.537    13889577.777
     3075278.469    13889572.031     3073243.175     13889747.02
#Sta/Elev= 30
       0   98.19  782.56    98.1 1186.79   96.64  1310.8   97.83 1709.95   96.78
 1725.41   96.18 1728.43   96.04 1770.93   87.95 1773.44   87.19 1777.29   82.47
 1780.31   82.03 1790.34   86.08 1812.37   90.87 1819.22   93.53 1828.34   95.25
 1848.44   96.68 1883.52   97.35  2005.2   96.15 2058.45   95.71  2472.3    98.5
 2636.83  100.94 2767.21  100.98 2920.35    98.8 3353.97  102.01 3607.27  102.01
 3682.37  100.96  4002.2  101.96 4160.61  100.75 4287.28  102.58 4663.27  103.06
#Mann= 5 ,-1 , 0
       0     .08       0 1709.95     .06       0 1725.41     .08       0
 1848.44     .06       0  2005.2     .08       0
#XS Ineff= 4 ,-1
  207.79  522.94   98.38  824.23 1309.07   97.84 1883.63 2145.53   97.33
 2164.24 2295.19   97.53
Permanent Ineff=
       F       F       F       F
#Block Obstruct= 2 , 0
          204.33   98.53
Bank Sta=1728.43,1848.44
Exp/Cntr=0.3,0.1

Type RM Length L Ch R = 1 ,6898.815,909.08,915.81,914.45
BEGIN DESCRIPTION:
E122-00-V15 (Survey 1827.7 to 1979.81)
END DESCRIPTION:
XS GIS Cut Line= 6
     3078060.878    13889291.733     3076340.856    13889240.474
       3076240.9    13889237.495     3076066.088    13889232.286
     3075966.132    13889229.307     3073786.909    13889164.363
#Sta/Elev= 30
       0   98.12 1161.77   97.27 1498.46   96.07 1596.19   94.92 1795.86   95.83
  1827.7   95.12 1865.74   95.59 1881.38   87.66 1892.73   87.23 1904.57    81.3
 1908.57   80.97  1915.6   86.93 1929.83   88.09 1949.85   96.04 2011.31   97.47
 2399.98   98.34 2545.71   98.06 2881.45  100.28 3016.75  100.06 3046.76    99.1
 3099.11  100.66 3184.67   99.96 3448.88  101.06 3489.33  100.17 3640.48  100.98
 3855.07   99.99 3922.46   101.4 4148.67  102.51 4241.62  102.03 4275.87  100.73
#Mann= 5 ,-1 , 0
       0     .08       0 1795.86     .06       0 1865.74     .08       0
 1949.85     .06       0 2399.98     .08       0
#XS Ineff= 3 ,-1
  422.92  779.06   97.88 1509.97 1807.68   95.98 1818.81 1863.33    95.6
Permanent Ineff=
       F       F       F
#Block Obstruct= 2 , 0
           72.34   98.16
Bank Sta=1865.74,1949.85
Exp/Cntr=0.3,0.1

Type RM Length L Ch R = 1 ,5983.005,554.169,551.039,542.586
BEGIN DESCRIPTION:
E122-00-V16 (Survey 2233.55 to 2404.95)
END DESCRIPTION:
XS GIS Cut Line= 6
      3078492.13    13888483.559     3076375.392    13888336.778
     3076275.631     13888329.86     3076117.027    13888318.862
     3076017.266    13888311.944     3074657.313    13888217.641
#Sta/Elev= 30
       0   95.53  516.87   96.78  646.09   96.57  691.32   95.74  789.09   96.35
  852.63   95.11  887.21   95.54  995.37   94.64 1105.81   94.61 1215.93   95.94
  2191.1   93.89 2233.55   93.87 2265.55   94.71 2281.65   86.56 2295.68    85.3
 2300.81   81.41 2301.74   80.15 2306.52   79.25  2311.5   81.58 2316.42   85.22
 2331.23   86.62 2347.31   95.01 2404.95   96.35 2523.83   96.15 2608.26   97.43
 3028.49   98.94 3421.18   98.12 3502.44   97.93  3541.6   98.76 3844.03   98.03
#Mann= 5 ,-1 , 0
       0     .08       0  2191.1     .06       0 2265.55     .08       0
 2347.31     .06       0 3421.18     .08       0
#XS Ineff= 2 , 0
         2264.23   94.72 3123.52           99.14
Permanent Ineff=
       F       F
Bank Sta=2265.55,2347.31
Exp/Cntr=0.5,0.3

Type RM Length L Ch R = 1 ,5431.968,80.601,83.961,79.494
BEGIN DESCRIPTION:
E122-00-V16 (Survey 2233.55 to 2404.95 copied from section 5983. Elevations of survey data adjusted to fit stream slope).
END DESCRIPTION:
XS GIS Cut Line= 6
     3078656.303    13887845.789     3076534.784    13887809.991
     3076434.798    13887808.304     3076275.836    13887805.621
      3076175.85    13887803.934     3074812.825    13887780.935
#Sta/Elev= 30
       0   94.02  109.76   94.17  182.23   92.09  212.24   93.76  272.14    94.2
 1293.61    93.6 1393.28   92.48 1592.43   94.11 1967.49   93.49  2072.8   92.88
 2117.51    91.1 2229.54   93.29 2267.87   93.61 2267.98   92.51 2271.82   89.95
 2275.98   85.46 2283.95    84.2 2304.01   78.17 2308.78   78.15 2318.68   84.12
 2341.36   93.91 2407.08   96.35 2426.01   93.93 2525.95    93.6  2747.6   95.26
 2837.61   94.92 2964.81   96.61  3536.5   96.94 3629.58   96.36 3844.03   97.61
#Mann= 5 ,-1 , 0
       0     .08       0 2229.54     .06       0 2267.87     .08       0
 2341.36     .06       0  3536.5     .08       0
#XS Ineff= 2 , 0
         2268.02   93.65 2406.51           96.39
Permanent Ineff=
       F       F
Bank Sta=2267.87,2341.36
Exp/Cntr=0.5,0.3

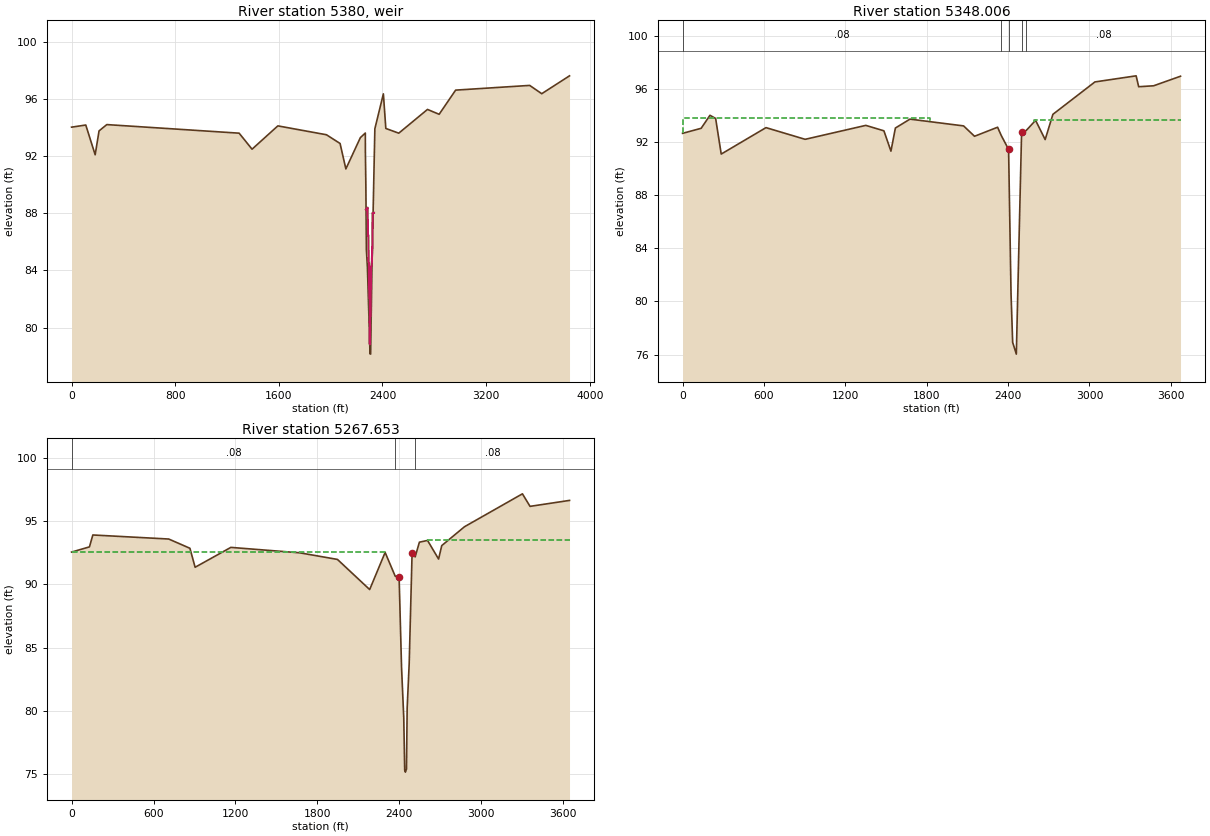
Type RM Length L Ch R = 5 ,5380    ,,,
BEGIN DESCRIPTION:
Inline weir, structure 11 - Shape taken from survey of structure
END DESCRIPTION:
IW Pilot Flow=0
#Inline Weir SE= 18
    2272  88.259 2286.02  88.393 2287.02  86.425 2292.01  86.461 2293.01  84.587
 2297.03  84.517 2297.03  82.727 2301.01  82.805 2302.03  81.388 2302.03  78.836
 2307.01  81.218 2307.01  82.728 2312.03  82.713 2312.03  84.245 2316.03  84.275
 2322.03  85.599 2323.03  88.034    2335  88.034
IW Dist,WD,Coef,Skew,MaxSub,Min_El,Is_Ogee,SpillHt,DesHd
45,1,2.6,0,0.95,, 0 ,,,0,0,

Type RM Length L Ch R = 1 ,5348.006,80.34,80.35,78.43
BEGIN DESCRIPTION:
E122-00-S11 (Survey 2403.54 to 2499.54)
END DESCRIPTION:
XS GIS Cut Line= 6
     3078795.461    13887746.543     3076516.288    13887728.088
     3076416.291    13887727.279     3076273.316    13887726.121
     3076173.319    13887725.311     3075124.561    13887716.819
#Sta/Elev= 30
       0   92.65  137.17   93.03   202.1   94.01  243.92   93.77  285.01   91.09
  615.02   93.08   903.8    92.2  1350.8   93.25 1484.49   92.84 1536.23   91.31
    1569   93.05 1676.43   93.72 2071.76   93.21 2152.44   92.43  2322.5   93.11
 2349.45   92.49 2403.54   91.44 2421.53    80.6 2433.53   76.92 2460.54   76.03
 2499.54   92.77    2533   92.86 2602.57   93.63 2673.24   92.18 2730.09   94.08
 3039.97   96.52 3343.74   96.98 3362.62   96.16 3472.76   96.23 3671.02   96.95
#Mann= 5 ,-1 , 0
       0     .08       0 2349.45     .04       0 2403.54    .015       0
 2499.54     .04       0    2533     .08       0
#XS Ineff= 2 , 0
         1820.88   93.84 2588.24           93.69
Permanent Ineff=
       F       F
Bank Sta=2403.54,2499.54
Exp/Cntr=0.5,0.3

Type RM Length L Ch R = 1 ,5267.653,503.58,505.14,506.35
BEGIN DESCRIPTION:
E122-00-SV11 (Survey 2397.82 to 2513.91)
END DESCRIPTION:
XS GIS Cut Line= 6
      3078791.84    13887628.789     3076520.919    13887646.058
     3076420.922    13887646.819     3076268.685    13887647.976
     3076168.688    13887648.737     3075146.468     13887656.51
#Sta/Elev= 30
       0   92.54  130.99   92.95  155.79   93.89  711.43   93.57   866.4   92.84
  904.56   91.34 1166.21   92.91 1671.18   92.48 1946.43   91.96 2182.38   89.58
 2295.59   92.51 2369.56   90.63 2397.92   90.56 2415.91    83.4 2431.91   79.47
  2438.9   75.31 2443.91   75.16 2451.88    75.4  2456.9   80.22 2471.91   83.78
 2492.92   92.46 2515.38   92.16 2546.45   93.32 2605.98   93.46 2686.96   91.99
 2710.07   93.05 2876.46   94.54 3300.76   97.14 3356.47   96.15 3645.48   96.62
#Mann= 3 ,-1 , 0
       0     .08       0 2369.56     .04       0 2515.38     .08       0
#XS Ineff= 3 ,-1
       0 2295.02   92.53 2492.84 2523.59   92.46 2605.18 3645.48   93.48
Permanent Ineff=
       F       F       F
Bank Sta=2397.92,2492.92
Exp/Cntr=0.3,0.1