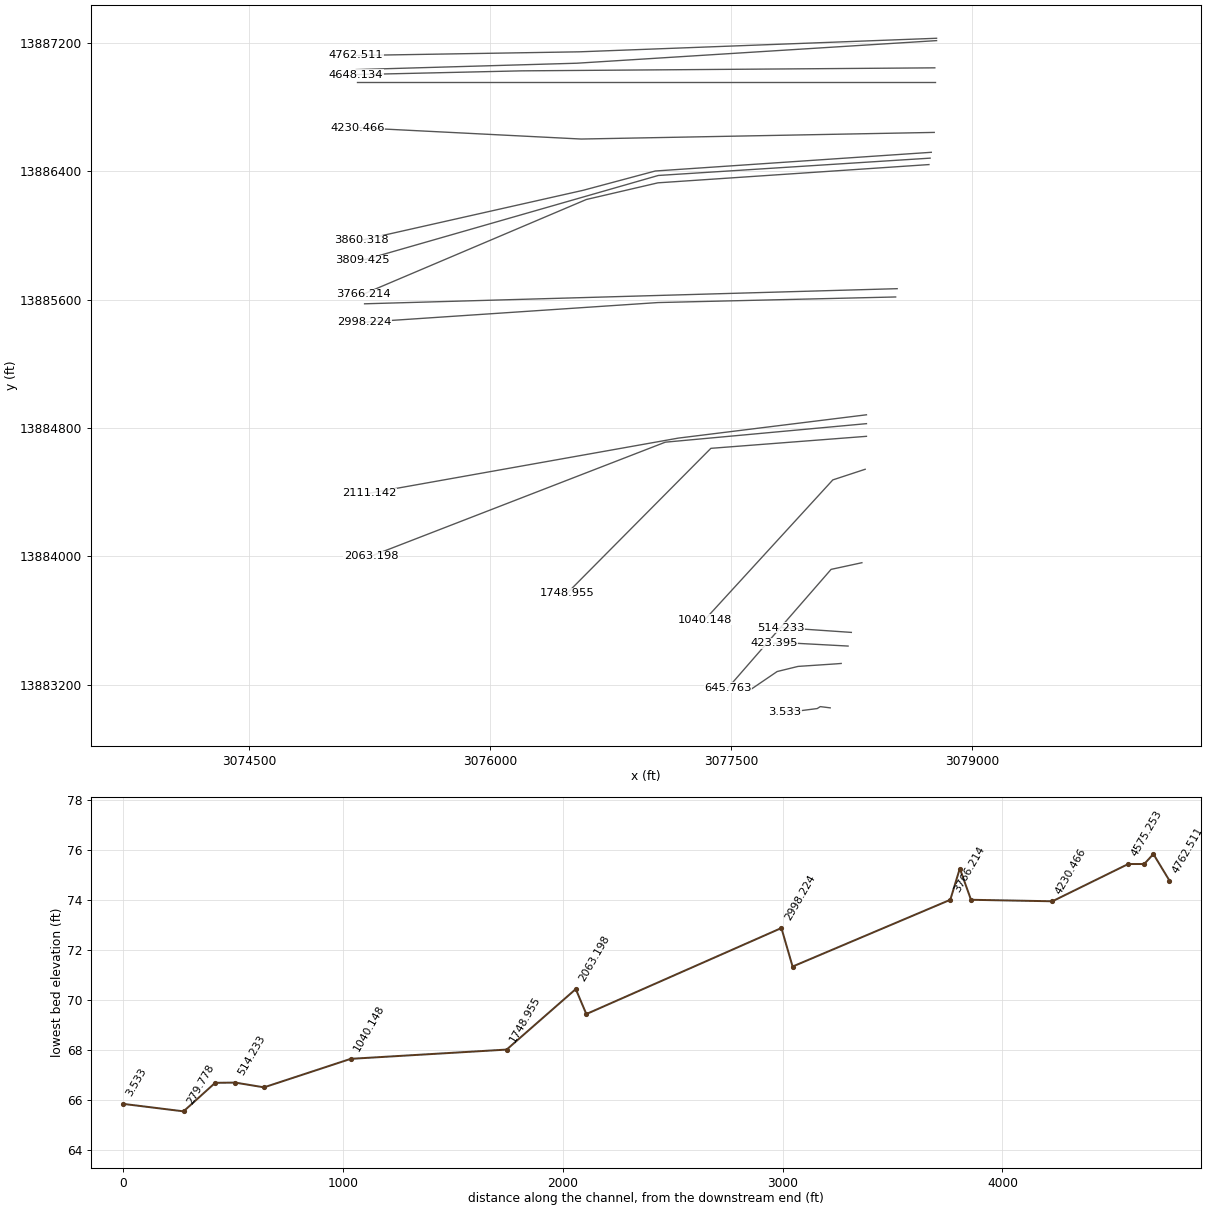
HEC-RAS study E122-00-00.prj: E122-00-00

--- E122-00-00.g08 (geometry) --- (continued)

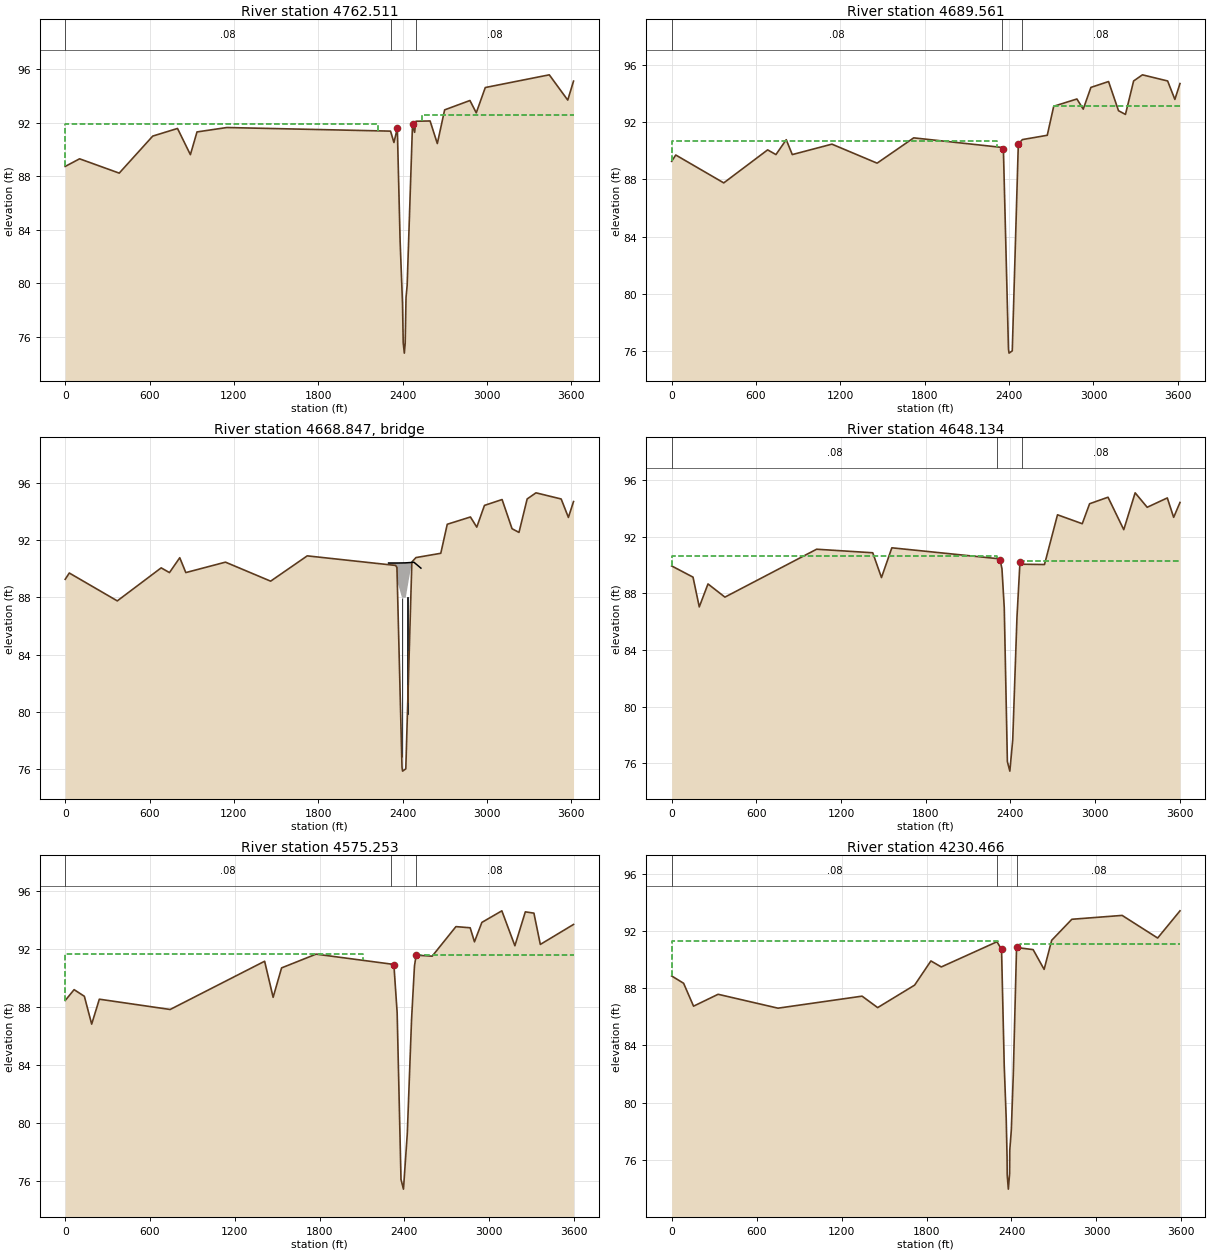
Type RM Length L Ch R = 1 ,4762.511,72.12,72.95,74.96
BEGIN DESCRIPTION:
E122-00-SV12 (Survey 2327.54 to 2491.61) XS 4
END DESCRIPTION:
XS GIS Cut Line= 6
     3078777.961    13887230.484     3076556.797    13887146.017
     3076456.811    13887144.378     3076280.262    13887141.484
     3076180.275    13887139.844     3075163.603    13887123.178
#Sta/Elev= 30
       0   88.75  102.42   89.32  384.26   88.25  622.79   91.02  798.88   91.59
  890.59   89.63  937.55   91.33 1149.91   91.66 2314.34   91.39  2338.6   90.54
 2362.61   91.61 2382.58   83.15 2399.61   78.51 2404.61   75.56 2412.59   74.79
 2418.57   75.53 2424.54   78.95 2432.54   79.85 2470.62    91.9 2485.63    91.3
 2495.14   92.13 2595.73   92.15 2647.24   90.46 2699.17   92.98 2879.19   93.68
  2924.2   92.76 2988.38   94.65 3443.68    95.6 3574.99   93.71 3616.15   95.13
#Mann= 3 ,-1 , 0
       0     .08       0 2314.34     .04       0 2495.14     .08       0
#XS Ineff= 2 , 0
         2226.48   91.95 2536.55           92.59
Permanent Ineff=
       F       F
Bank Sta=2362.61,2470.62
Exp/Cntr=0.5,0.3

Type RM Length L Ch R = 1 ,4689.561,42.83,41.43,40.03
BEGIN DESCRIPTION:
E122-00-S12 (Survey 2359.4 to 2465.53) XS 3
END DESCRIPTION:
XS GIS Cut Line= 6
     3078777.961    13887215.899     3076539.404    13887074.913
     3076439.445    13887072.022     3076299.364     13887067.97
     3076199.406    13887065.078     3075167.538    13887035.231
#Sta/Elev= 30
       0   89.27   29.11   89.71  370.48   87.76  682.59   90.07   741.6   89.74
  814.79   90.78  857.85   89.74 1139.79   90.47  1461.1   89.14 1721.53   90.91
 2350.03   90.24  2359.4    90.1 2395.53   76.12 2399.65   75.85 2422.43   76.01
 2465.53   90.48 2494.65   90.79 2671.32   91.09 2717.31   93.12  2882.2   93.63
 2927.22   92.92 2981.79   94.44 3107.29   94.85 3178.08   92.81 3227.49   92.55
 3285.55   94.89 3348.27   95.32 3527.47   94.89 3579.01    93.6 3615.43   94.71
#Mann= 3 ,-1 , 0
       0     .08       0 2350.03     .04       0 2494.65     .08       0
#XS Ineff= 2 , 0
         2315.35   90.72  2716.3           93.13
Permanent Ineff=
       F       F
Bank Sta=2359.4,2465.53
Exp/Cntr=0.5,0.3

Type RM Length L Ch R = 3 ,4668.847,,,
BEGIN DESCRIPTION:
Structure 12 - Sawmill Road
END DESCRIPTION:
Bridge Culvert--1,0,-1,-1, 0
Deck Dist Width WeirC Skew NumUp NumDn MinLoCord MaxHiCord MaxSubmerge Is_Ogee
3.1,35.22,2.6,0, 5, 6, , , 0.95, 0, 0,0,,
    2300 2361.94 2418.96 2480.96 2529.98
   90.41   90.41   90.42   90.46   90.05
           87.98   87.99   88.03   87.62
    2300 2337.96 2394.98 2456.98    2506  2519.5
   90.41   90.41   90.42   90.46   90.05    89.9
           87.98   87.99   88.03   87.62
Pier Skew, UpSta & Num, DnSta & Num=  ,2393.74, 4 ,2377.08, 4 , 3 , 3 , 0 ,,
    1.35    1.35       2       2
      74    85.3    85.3      89
    1.35    1.35       2       2
      74    85.3    85.3      89
Pier Skew, UpSta & Num, DnSta & Num=  ,2433.76, 4 ,2417.09, 4 , 3 , 3 , 0 ,,
    1.35    1.35       2       2
      74    85.3    85.3      89
    1.35    1.35       2       2
      74    85.3    85.3      89
BR Coef=-1 , 1 , 1 ,1.25, 0 ,,,0.8,-1,2,0,
WSPro=,,,, 1 ,,,, 0 ,,,, 0 ,,,,-1 ,-1 ,-1 , 0 , 0 , 0 , 0 , 0
BC Design=,, 0 ,, 0 ,,,,,,
BC HTab HWMax=95.32

Type RM Length L Ch R = 1 ,4648.134,73.32,72.88,72.37
BEGIN DESCRIPTION:
Survey 2378.74 (S12) to 2396.1 XS 2
END DESCRIPTION:
XS GIS Cut Line= 6
     3078767.037    13887046.086     3076548.072    13887029.889
     3076448.075    13887029.159     3076295.685    13887028.047
     3076195.688    13887027.317     3075165.559    13887003.911
#Sta/Elev= 30
       0   89.93  151.28   89.14  195.54   87.04  257.42   88.66  377.26   87.73
 1027.03   91.11 1424.63   90.86 1486.61   89.11 1560.08   91.21 2305.16   90.45
 2326.63   90.36 2340.27   89.74 2356.63   86.97 2378.74   76.12  2396.1   75.45
 2416.64   77.66 2446.64    86.3 2467.86   90.18 2485.25   90.05 2641.66   90.03
  2733.9   93.54 2909.31   92.91 2961.27   94.32 3091.78   94.78 3203.36   92.49
 3284.02   95.09 3369.39   94.07 3511.88   94.73  3556.9   93.36 3601.81   94.41
#Mann= 3 ,-1 , 0
       0     .08       0 2305.16     .04       0 2485.25     .08       0
#XS Ineff= 2 , 0
         2302.07   90.62 2468.21           90.31
Permanent Ineff=
       F       F
Bank Sta=2326.63,2467.86
Exp/Cntr=0.5,0.3

Type RM Length L Ch R = 1 ,4575.253,347.98,344.79,340.45
BEGIN DESCRIPTION:
Survey 2376.6 (2378.74) to 2393.97 (2396.1) from 4648 XS 1
END DESCRIPTION:
XS GIS Cut Line= 6
     3078767.022    13886955.745     3076558.086    13886955.745
     3076458.086    13886955.745      3076297.91    13886955.745
      3076197.91    13886955.745     3075169.427    13886955.745
#Sta/Elev= 30
       0   88.47   63.05   89.22  135.56   88.76  187.36   86.84  241.56   88.56
  742.76   87.85 1411.31   91.18 1471.56   88.69 1531.31   90.72 1775.53   91.67
 2302.46   90.99 2326.56   90.89 2349.31   87.62  2376.6   76.12 2393.97   75.45
 2421.23   79.31 2451.23   87.16 2471.89   90.85 2483.56    91.6  2597.3   91.53
 2765.35   93.57 2866.06   93.49 2896.56   92.52 2948.81   93.86 3090.23   94.66
 3182.55   92.25 3256.45   94.59 3317.22    94.5 3362.55   92.34  3597.6   93.72
#Mann= 3 ,-1 , 0
       0     .08       0 2302.46     .04       0 2483.56     .08       0
#XS Ineff= 2 , 0
         2109.53   91.66 2484.02           91.61
Permanent Ineff=
       F       F
Bank Sta=2326.56,2483.56
Exp/Cntr=0.3,0.1

Type RM Length L Ch R = 1 ,4230.466,351.54,370.15,389.28
BEGIN DESCRIPTION:
E122-00-SV13 (Survey 2302.08 to 2461.13)
END DESCRIPTION:
XS GIS Cut Line= 6
     3078763.376    13886643.436     3076566.522    13886602.128
     3076466.651    13886607.206     3076295.891    13886615.889
      3076196.02    13886620.967     3075175.309    13886672.867
#Sta/Elev= 30
       0   88.85   84.26   88.34  154.55   86.74  327.97   87.57  750.97    86.6
 1344.72   87.44 1454.94   86.64 1715.99   88.21 1830.96    89.9 1904.27   89.48
 2297.76   91.24 2329.89    90.7 2348.82    82.6  2362.8   78.89 2368.84    76.2
 2369.84   74.96 2377.83   73.96 2386.92   75.06 2387.92   76.67 2398.85   78.09
 2412.88   81.97 2435.96   90.87 2441.37   90.83 2553.03   90.69 2630.59   89.31
 2683.88   91.34 2826.45   92.81  3181.6   93.08 3432.43    91.5 3590.25    93.4
#Mann= 3 ,-1 , 0
       0     .08       0 2297.76     .04       0 2441.37     .08       0
#XS Ineff= 2 , 0
         2302.36   91.27 2461.23           91.05
Permanent Ineff=
       F       F
Bank Sta=2329.89,2435.96
Exp/Cntr=0.3,0.1

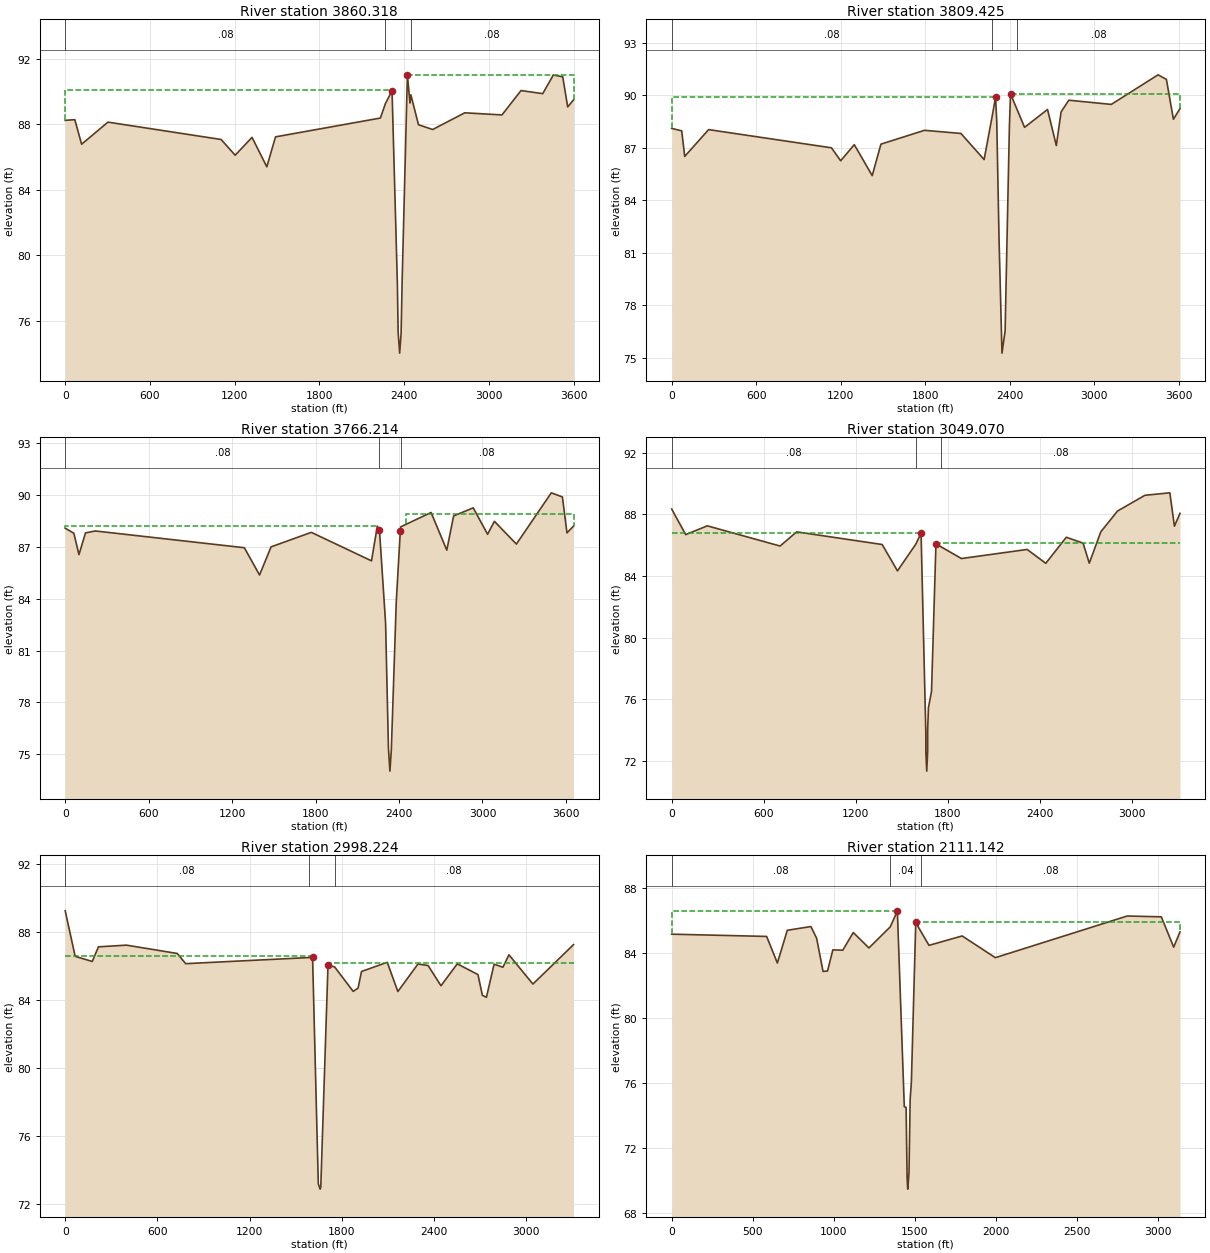
Type RM Length L Ch R = 1 ,3860.318,47.01,50.89,54.93
BEGIN DESCRIPTION:
E122-00-SV14 (Survey 2293.99 to 2445.4)
END DESCRIPTION:
XS GIS Cut Line= 6
     3078745.145    13886519.463     3077027.757    13886402.783
     3076579.245    13886282.502     3076481.701    13886260.476
     3076320.203    13886224.008     3075200.206    13885971.106
#Sta/Elev= 30
       0   88.24   68.11   88.28  116.16   86.78  302.59   88.13 1103.96   87.07
 1203.59   86.11 1322.94    87.2 1427.48    85.4 1489.28   87.23 2231.83   88.38
 2267.66   89.27 2314.37   90.05 2352.23   78.22 2357.33   75.32 2368.28   74.02
 2378.47   75.22 2385.52   78.32 2423.06   91.01 2441.28    89.3 2447.64    89.8
 2501.66   87.97 2602.25   87.68  2829.3    88.7 3092.74   88.57 3227.59   90.06
 3381.32   89.87 3456.54   91.01 3522.94    90.9 3558.19   89.06 3599.47   89.49
#Mann= 3 ,-1 , 0
       0     .08       0 2267.66     .04       0 2447.64     .08       0
#XS Ineff= 2 , 0
         2314.52   90.07 2423.17           91.02
Permanent Ineff=
       F       F
Bank Sta=2314.37,2423.06
Exp/Cntr=0.3,0.1

Type RM Length L Ch R = 1 ,3809.425,34.48,43.21,51.28
BEGIN DESCRIPTION:
E122-00-S14 (Survey 2299.79 to 2406.11)
END DESCRIPTION:
XS GIS Cut Line= 6
     3078737.852    13886483.001     3077046.649    13886374.963
     3076579.543    13886240.645     3076483.438     13886213.01
     3076252.461    13886146.592     3075206.497    13885845.821
#Sta/Elev= 30
       0   88.11   71.19   87.97   92.75   86.51  262.45   88.04 1134.65      87
 1199.92   86.26 1296.79   87.18 1423.94   85.41  1485.9   87.21 1795.48      88
 2053.79   87.82 2218.59   86.33  2273.9   88.72 2299.79   89.88 2308.31   88.49
 2324.23   81.87 2345.39   75.27 2367.51   76.53 2398.14   88.26 2406.11   90.08
 2505.63   88.17 2668.77   89.19  2731.2   87.13 2765.05   89.05 2819.79   89.72
  3121.4   89.48 3453.67   91.17  3512.8   90.91 3562.58   88.63 3609.37   89.24
#Mann= 3 ,-1 , 0
       0     .08       0  2273.9     .04       0 2454.37     .08       0
#XS Ineff= 2 , 0
         2299.31   89.89 2406.29           90.09
Permanent Ineff=
       F       F
Bank Sta=2299.79,2406.11
Exp/Cntr=0.3,0.1

Type RM Length L Ch R = 1 ,3766.214,744.71,717.14,688.48
BEGIN DESCRIPTION:
Survey 2324.02 to 2344.52 (2293.99 to 2445.4 from SV14)
END DESCRIPTION:
XS GIS Cut Line= 6
      3078730.56    13886442.892     3077044.483    13886329.025
     3076599.049    13886225.155     3076507.028    13886186.011
     3076357.976    13886122.608        3075212.    13885635.141
#Sta/Elev= 30
       0   88.09    62.2    87.8   98.82   86.56  145.95   87.82  217.11   87.93
 1288.02   86.96 1397.27   85.38 1480.07   87.01 1769.46   87.85  2202.2    86.2
  2243.9   88.21 2259.38   87.98 2303.34   82.61 2324.02   75.32 2334.53   74.02
 2344.52   75.22 2380.22   83.84 2409.28   87.92 2412.05   88.17 2630.58      89
 2743.45   86.82 2792.36    88.8 2933.45   89.27 3036.78   87.74 3085.77   88.49
 3243.76   87.17 3494.83   90.14 3574.79    89.9 3607.39   87.82 3654.62   88.21
#Mann= 3 ,-1 , 0
       0     .08       0 2259.38     .04       0 2412.05     .08       0
#XS Ineff= 2 , 0
         2243.18   88.21 2448.37           88.92
Permanent Ineff=
       F       F
Bank Sta=2259.38,2409.28
Exp/Cntr=0.3,0.1

Type RM Length L Ch R = 1 ,3049.070,48.66,50.85,53.78
BEGIN DESCRIPTION:
E122-00-SV15 (Survey 1602.41 to 1751.46)
END DESCRIPTION:
XS GIS Cut Line= 6
     3078532.746    13885669.033     3077041.846    13885626.588
     3076941.886    13885623.742      3076779.23    13885619.111
      3076679.27    13885616.265     3075219.183    13885574.697
#Sta/Elev= 30
       0   88.34    91.5   86.68  232.38   87.25   707.3   85.94  814.92   86.86
 1372.84   86.04 1472.49   84.33 1591.15   86.05  1626.4   86.77 1657.41   73.84
 1657.44    72.6 1663.41   71.35 1669.47   72.67 1669.49   74.06 1674.52   75.47
 1694.57   76.52 1723.47    86.1  1756.9   85.89 1889.52   85.13 2318.22   85.72
 2439.73   84.82 2573.32   86.51 2682.92   86.13 2723.38   84.83 2798.41   86.86
 2907.56   88.21 3086.16   89.23  3248.6   89.39 3278.61   87.23 3314.91   88.06
#Mann= 3 ,-1 , 0
       0     .08       0 1591.15     .04       0  1756.9     .08       0
#XS Ineff= 2 , 0
         1625.95   86.77  1723.6           86.12
Permanent Ineff=
       F       F
Bank Sta=1626.4,1723.47
Exp/Cntr=0.3,0.1

Type RM Length L Ch R = 1 ,2998.224,874.19,887.08,891.42
BEGIN DESCRIPTION:
E122-00-S15 (Survey 1609.95 to 1710.26)
END DESCRIPTION:
XS GIS Cut Line= 6
     3078523.331    13885617.319     3077043.398    13885582.402
     3076943.623    13885575.697     3076797.174    13885565.857
     3076697.399    13885559.153     3075219.605    13885459.854
#Sta/Elev= 30
       0   89.27    64.9   86.59  176.01   86.29  216.34   87.15  398.23   87.25
  729.46   86.76  784.02   86.16 1609.95   86.53  1647.2    73.2 1659.11   72.89
 1663.23   73.01 1710.26   86.07 1753.37   85.97 1874.16   84.53 1906.02   84.72
 1928.35    85.7 2095.87   86.24 2164.94   84.52 2295.86   86.14 2361.83   86.05
 2445.61   84.86 2551.59   86.15 2686.08   85.52    2715    84.3  2741.4   84.18
 2791.23   86.13 2848.59   85.95 2887.88   86.68 3043.88   84.96 3308.25   87.28
#Mann= 3 ,-1 , 0
       0     .08       0 1587.96     .04       0 1753.37     .08       0
#XS Ineff= 2 , 0
         1608.19   86.62 1711.58           86.18
Permanent Ineff=
       F       F
Bank Sta=1609.95,1710.26
Exp/Cntr=0.3,0.1

Type RM Length L Ch R = 1 ,2111.142,33.06,47.94,59.69
BEGIN DESCRIPTION:
E122-00-SV16 (Survey 1370.46 to 1530.01)
END DESCRIPTION:
XS GIS Cut Line= 6
     3078341.625    13884882.598     3077171.535    13884737.292
     3077086.635    13884722.121     3076819.749     13884674.43
     3076721.308    13884656.839     3075247.065      13884393.4
#Sta/Elev= 30
       0   85.18  585.62   85.04  651.68    83.4  712.93   85.42  858.44   85.65
   893.7   84.93  933.27   82.88  960.92   82.91  993.73   84.21 1054.93   84.19
 1119.78   85.28 1216.22   84.33 1347.63   85.63 1391.51   86.61  1434.2   74.54
 1445.38   74.49 1451.46   70.19 1455.58   69.45 1463.28   70.46 1470.34   74.99
 1477.76   76.02 1504.87    85.9 1535.68   85.36  1586.5   84.49  1790.9   85.07
 1995.56   83.73  2808.5    86.3 3018.84   86.25 3095.02   84.38 3134.03   85.32
#Mann= 3 ,-1 , 0
       0     .08       0 1347.63     .04       0 1535.68     .08       0
#XS Ineff= 2 , 0
         1390.63   86.62 1505.24           85.91
Permanent Ineff=
       F       F
Bank Sta=1391.51,1504.87
Exp/Cntr=0.3,0.1

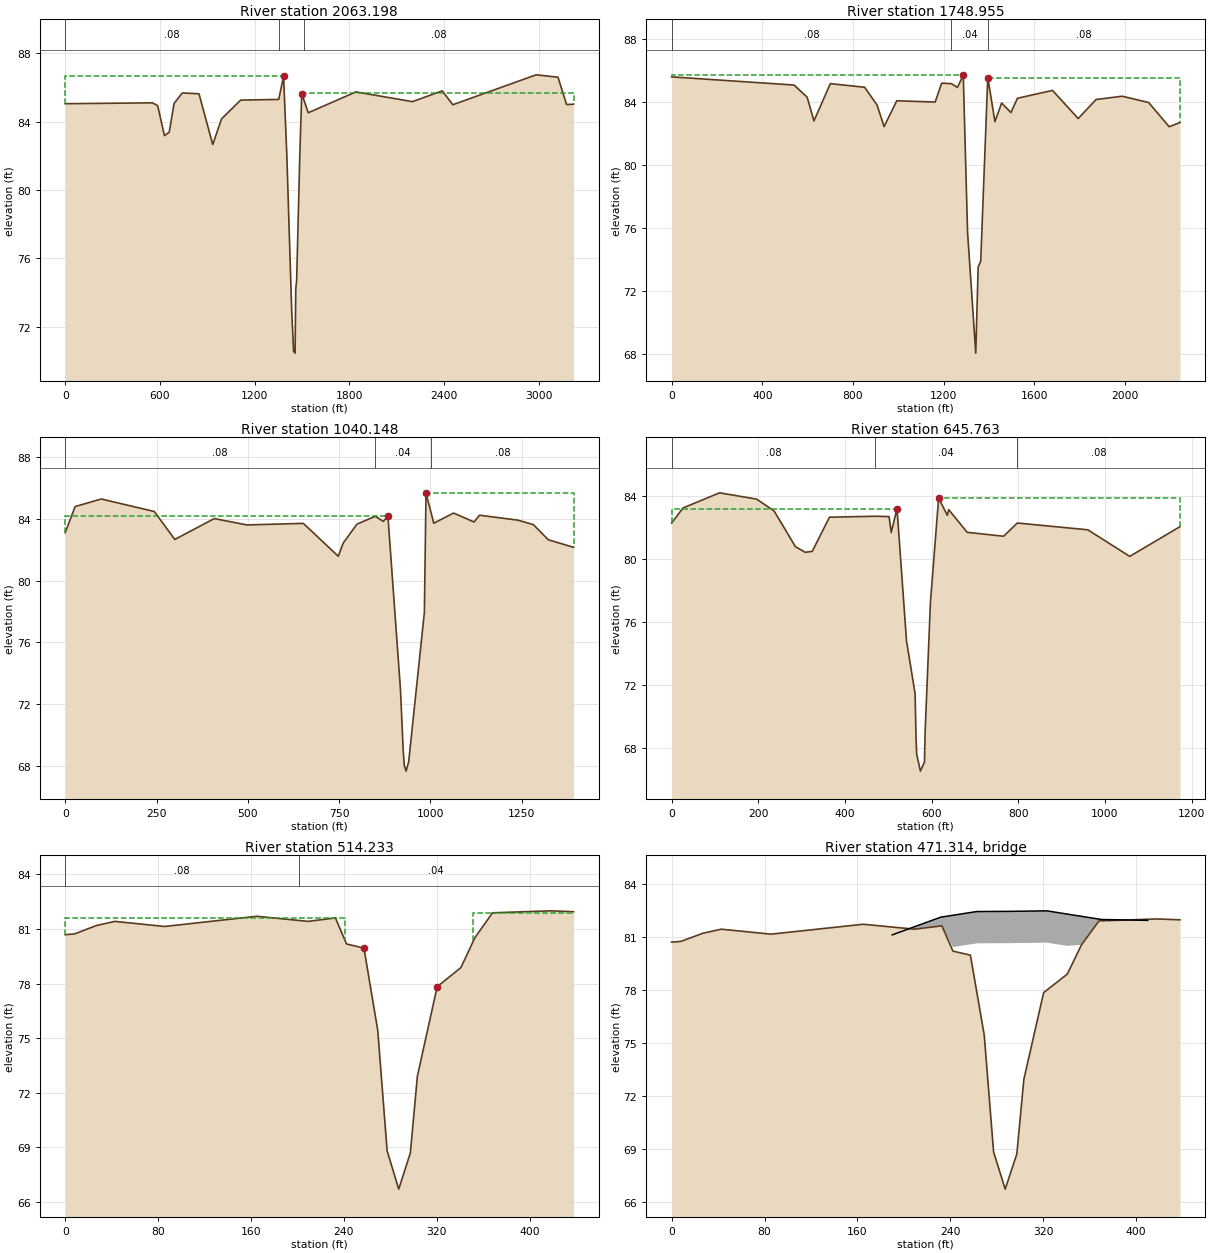
Type RM Length L Ch R = 1 ,2063.198,276.73,314.24,338.07
BEGIN DESCRIPTION:
E122-00-S16 (Survey 1383.51 to 1498.45) Pipeline
END DESCRIPTION:
XS GIS Cut Line= 6
     3078341.625    13884827.296     3077090.098    13884711.779
     3076996.877    13884675.587      3076849.27    13884618.281
     3076756.049     13884582.09     3075259.646    13884001.133
#Sta/Elev= 30
       0   85.05  552.63    85.1  585.71   84.94  628.82   83.18  658.95   83.38
  689.55   85.06  741.93   85.68  847.65   85.63  934.76   82.66  990.35   84.16
 1111.62   85.26 1352.57    85.3 1383.51   86.65 1404.27   81.98 1435.13   72.86
 1446.83   70.57 1456.31   70.45 1460.71   74.22 1466.15   74.69 1486.18   81.98
 1498.45   85.64 1539.77   84.52  1841.9   85.74 2200.09   85.17 2388.17    85.8
  2455.7   84.99 2983.53   86.74  3122.1    86.6 3176.32      85 3220.41   85.02
#Mann= 3 ,-1 , 0
       0     .08       0 1352.57     .04       0 1513.59     .08       0
#XS Ineff= 2 , 0
         1382.59   86.67 1499.04           85.66
Permanent Ineff=
       F       F
Bank Sta=1383.51,1498.45
Exp/Cntr=0.3,0.1

Type RM Length L Ch R = 1 ,1748.955,705.17,708.81,710.72
BEGIN DESCRIPTION:
E122-00-V17 (Survey 1261.54 to 1400.85)
END DESCRIPTION:
XS GIS Cut Line= 6
     3078341.625    13884748.294     3077373.631    13884673.418
     3077246.103    13884544.627     3077058.814    13884355.484
     3076988.452    13884284.426     3076478.092    13883769.013
#Sta/Elev= 30
       0   85.59  540.25   85.07  597.94    84.3  628.03   82.79  700.32   85.16
  851.74   84.93  906.55    83.8  937.63   82.43  993.56   84.07 1163.08   83.99
 1191.71   85.19 1234.01   85.16 1261.54   84.92 1286.99   85.71 1306.11   75.69
 1342.15   68.03 1352.75   73.49 1364.06   73.87  1395.2   85.55 1426.87   82.74
 1456.36   83.93 1497.52   83.32 1525.99   84.23 1680.92   84.73 1794.41   82.94
 1873.14   84.15 1988.35   84.36 2105.26   83.96 2195.85   82.42 2243.65   82.69
#Mann= 3 ,-1 , 0
       0     .08       0 1234.01     .04       0  1395.2     .08       0
#XS Ineff= 2 , 0
         1286.19   85.72 1395.43           85.55
Permanent Ineff=
       F       F
Bank Sta=1286.99,1395.2
Exp/Cntr=0.3,0.1

Type RM Length L Ch R = 1 ,1040.148,391.3,394.39,393.59
BEGIN DESCRIPTION:
E122-00-V18 (Survey 870.81 to 1008.97)
END DESCRIPTION:
XS GIS Cut Line= 6
     3078333.725    13884542.888     3078132.448    13884476.597
     3077774.575    13884084.896     3077707.124    13884011.069
     3077523.325    13883809.895     3077336.723    13883605.655
#Sta/Elev= 30
       0   83.11   27.15    84.8   98.82   85.29  243.88   84.48  299.98   82.67
  408.06   84.02  497.67   83.61  651.94   83.71  747.63   81.58  761.03   82.43
  798.64   83.66  848.89   84.17  870.81   83.84  883.52   84.16  917.75   72.97
  925.42   68.99  928.25   68.03  933.22   67.66  940.29   68.26  983.28   77.94
  987.78   85.67 1001.97   84.37 1008.97   83.72 1063.45   84.38 1119.23    83.8
 1134.31   84.24 1239.23   83.92 1281.79   83.63 1322.43   82.65 1391.62   82.16
#Mann= 3 ,-1 , 0
       0     .08       0  848.89     .04       0 1001.97     .08       0
#XS Ineff= 2 , 0
          882.89   84.18  988.14           85.69
Permanent Ineff=
       F       F
Bank Sta=883.52,987.78
Exp/Cntr=0.3,0.1

Type RM Length L Ch R = 1 ,645.763 ,186.18,131.53,85.26
BEGIN DESCRIPTION:
E122-00-SV17 (Survey 501.74 to 616.15) XS 4
END DESCRIPTION:
XS GIS Cut Line= 6
     3078313.343    13883960.168     3078121.676    13883918.647
     3077999.596     13883778.05     3077934.033    13883702.542
     3077765.435     13883508.37     3077481.051    13883180.849
#Sta/Elev= 30
       0   82.29   26.33   83.25  110.47   84.21  196.11   83.81   236.6   83.05
  285.57   80.79   308.2   80.43  324.46   80.49  364.19   82.66  469.29   82.72
  501.74    82.7  506.73   81.69  520.08    83.2     542   74.81  561.85   71.44
  564.01   68.61  565.42   67.61  574.08   66.52   583.5    67.1  584.91   68.99
  597.25   77.26  616.15   83.88  636.18   82.78  639.47   83.14  682.03    81.7
  766.13   81.45  797.79   82.29  960.46   81.86 1057.21   80.17 1173.22   82.06
#Mann= 3 ,-1 , 0
       0     .08       0  469.29     .04       0  797.79     .08       0
#XS Ineff= 2 , 0
          518.77   83.21   615.7           83.88
Permanent Ineff=
       F       F
Bank Sta=520.08,616.15
Exp/Cntr=0.5,0.3

Type RM Length L Ch R = 1 ,514.233 ,89.91,90.84,93.09
BEGIN DESCRIPTION:
E122-00-S17 (Survey 257.29 to 320.35) XS 3. Point 287.24 added based on surrounding cross-sections. No survey point available for channel low point.
END DESCRIPTION:
XS GIS Cut Line= 5
     3078247.635     13883525.67     3078122.942     13883534.21
     3078023.176    13883541.044     3077896.408    13883549.726
     3077810.868    13883555.585
#Sta/Elev= 22
       0   80.69    7.97   80.73   26.85   81.19   42.73   81.42   85.63   81.14
  164.95    81.7  201.38   81.47   209.1   81.42  232.71   81.61  242.25   80.18
  257.29   79.95  269.19   75.43  277.24   68.82  287.24   66.71  297.26    68.7
  303.32   72.92  320.35   77.83  340.75   78.88     353   80.54  368.03   81.89
  418.16      82  437.79   81.95
#Mann= 2 ,-1 , 0
       0     .08       0  201.38     .04       0
#XS Ineff= 2 , 0
       0  240.81    81.6  351.56       0   81.89
Permanent Ineff=
       F       F
Bank Sta=257.29,320.35
Exp/Cntr=0.5,0.3

Type RM Length L Ch R = 3 ,471.314 ,,,
BEGIN DESCRIPTION:
Structures 17 and 18 - Gulf Bank Road
END DESCRIPTION:
Bridge Culvert--1,0,-1,-1, 0
Deck Dist Width WeirC Skew NumUp NumDn MinLoCord MaxHiCord MaxSubmerge Is_Ogee
0.52,89.8,2.6,0, 7, 5, 81.972, , 0.95, 0, 0,0,,
     190  231.68  262.82  291.88  323.02  370.11     410
    81.1    82.1   82.42   82.43   82.46   81.97   81.92
            80.3   80.62   80.63   80.66   80.17
  191.43  236.52  266.64  296.71  361.88
    81.7   82.23   82.32   82.24   81.82
    79.9   80.43   80.52   80.44   80.02
BR Coef=-1 , 1 , 0 ,1.2, 0 ,,,0.8,-1,2,0,
WSPro=,,,, 1 ,,,, 0 ,,,, 0 ,,,,-1 ,-1 ,-1 , 0 , 0 , 0 , 0 , 0
BC Design=,, 0 ,, 0 ,,,,,,
BC HTab HWMax=82

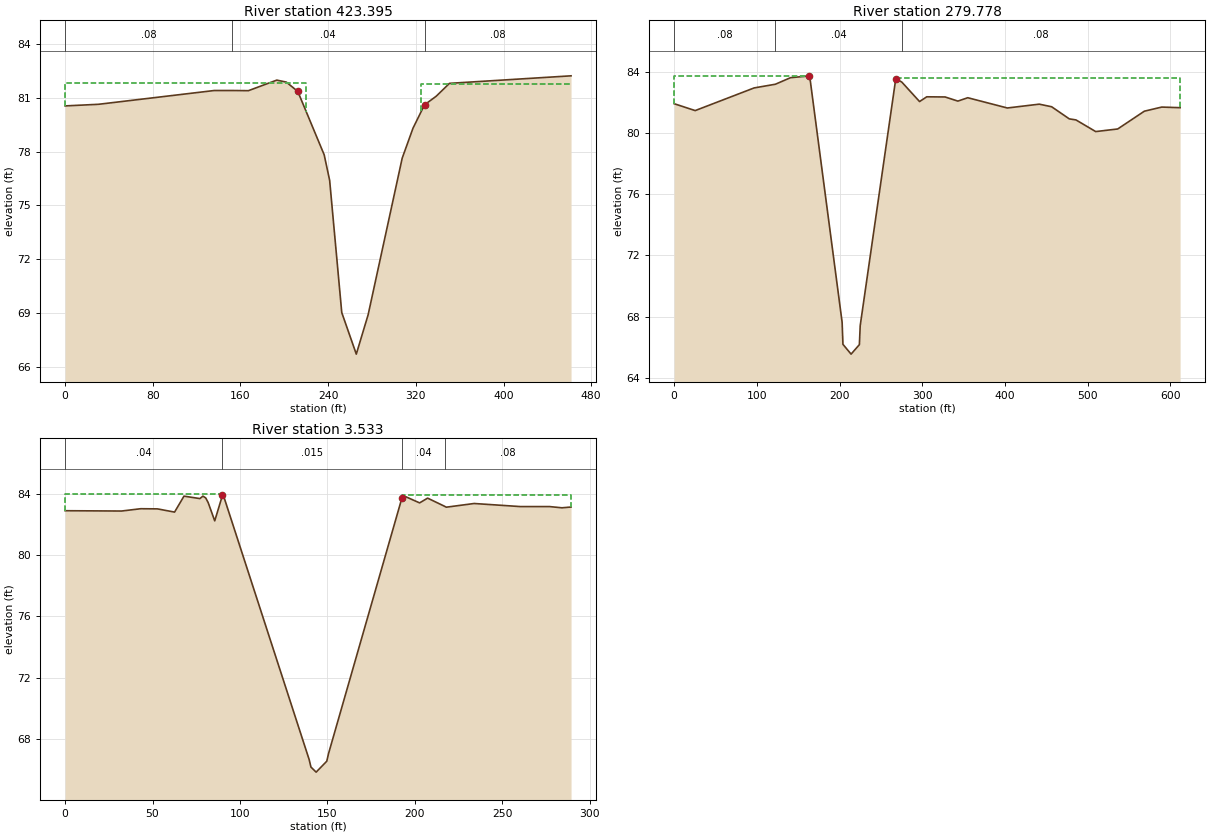
Type RM Length L Ch R = 1 ,423.395 ,131.84,143.62,148.54
BEGIN DESCRIPTION:
E122-00-S18 (Survey 236.38 to 276.48) XS 2
END DESCRIPTION:
XS GIS Cut Line= 6
     3078227.446    13883440.464     3078125.347    13883445.953
     3078025.491    13883451.322     3077917.825     13883457.11
     3077866.298     13883457.46     3077766.301     13883458.14
#Sta/Elev= 19
       0   80.56   30.48   80.65  136.14   81.42  152.33   81.42  167.22   81.41
  193.16      82  201.83   81.89  212.29   81.37  236.38   77.83  241.37    76.4
  252.41   69.02  265.68    66.7  276.48    68.9  307.54   77.64  317.43   79.32
  327.92   80.62  338.56    81.1  350.69   81.82   461.6   82.24
#Mann= 3 ,-1 , 0
       0     .08       0  152.33     .04       0  327.92     .08       0
#XS Ineff= 2 , 0
       0  220.02   81.86  324.98       0   81.77
Permanent Ineff=
       F       F
Bank Sta=212.29,327.92
Exp/Cntr=0.5,0.3

Type RM Length L Ch R = 1 ,279.778 ,267.07,276.24,273.85
BEGIN DESCRIPTION:
E122-00-V19 (Survey 140.82 to 279.18) XS 1
END DESCRIPTION:
XS GIS Cut Line= 6
     3078184.465    13883331.987      3078153.63    13883329.525
     3078053.855    13883322.818     3077916.089    13883313.556
     3077785.981      13883281.6     3077613.339    13883163.888
#Sta/Elev= 30
       0   81.91   25.45   81.46   96.73   82.94  122.39   83.18  140.82   83.61
  163.39   83.72   163.9   83.72  203.15   67.64  204.15    66.2  213.99   65.56
  224.04   66.18  225.03   67.42  268.14   83.58  268.64   83.53  275.37   83.32
  296.81   82.05   305.5   82.36   327.7   82.35  343.14   82.08   355.1    82.3
  402.99   81.63  441.58   81.88  456.58   81.71  477.89   80.92  486.01   80.85
  509.84   80.09  536.47   80.26  568.66   81.42  589.72   81.69  611.94   81.65
#Mann= 3 ,-1 , 0
       0     .08       0  122.39     .04       0  275.37     .08       0
#XS Ineff= 2 , 0
          163.25   83.73  268.37           83.57
Permanent Ineff=
       F       F
Bank Sta=163.39,268.64
Exp/Cntr=0.3,0.1

Type RM Length L Ch R = 1 ,3.533   ,1.53,3.53,3.96
BEGIN DESCRIPTION:
E122-00-V20 (Survey 67.99 to 207.32)
END DESCRIPTION:
XS GIS Cut Line= 6
     3078116.153    13883055.118     3078054.434    13883062.914
     3078035.332    13883050.759     3077918.404    13883035.708
     3077896.408    13883043.812     3077834.936    13883029.273
#Sta/Elev= 30
       0   82.88   32.31   82.86   43.26   83.01    52.8      83   62.61   82.79
   67.99   83.83   77.09   83.67   78.83   83.83   80.44   83.71   81.82   83.41
   85.58   82.22    89.7   83.77   89.99   83.88   90.24   83.98   139.6   66.67
  140.59   66.19  143.57   65.86  149.65   66.57  150.64   67.06  192.71   83.74
  193.06   83.88  202.74   83.39  207.32    83.7  217.01   83.17  217.99   83.11
  233.91   83.35  260.31   83.15  277.01   83.15  284.12   83.07  289.35   83.12
#Mann= 4 ,-1 , 0
       0     .04       0    89.7    .015       0  192.71     .04       0
  217.01     .08       0
#XS Ineff= 2 , 0
           90.24   83.98  192.72           83.88
Permanent Ineff=
       F       F
Bank Sta=89.99,192.71
Exp/Cntr=0.3,0.1

Chan Stop Cuts=-1
Use User Specified Reach Order=0
User Specified Reach Order=E122-00-00      ,E122-00-00_0000